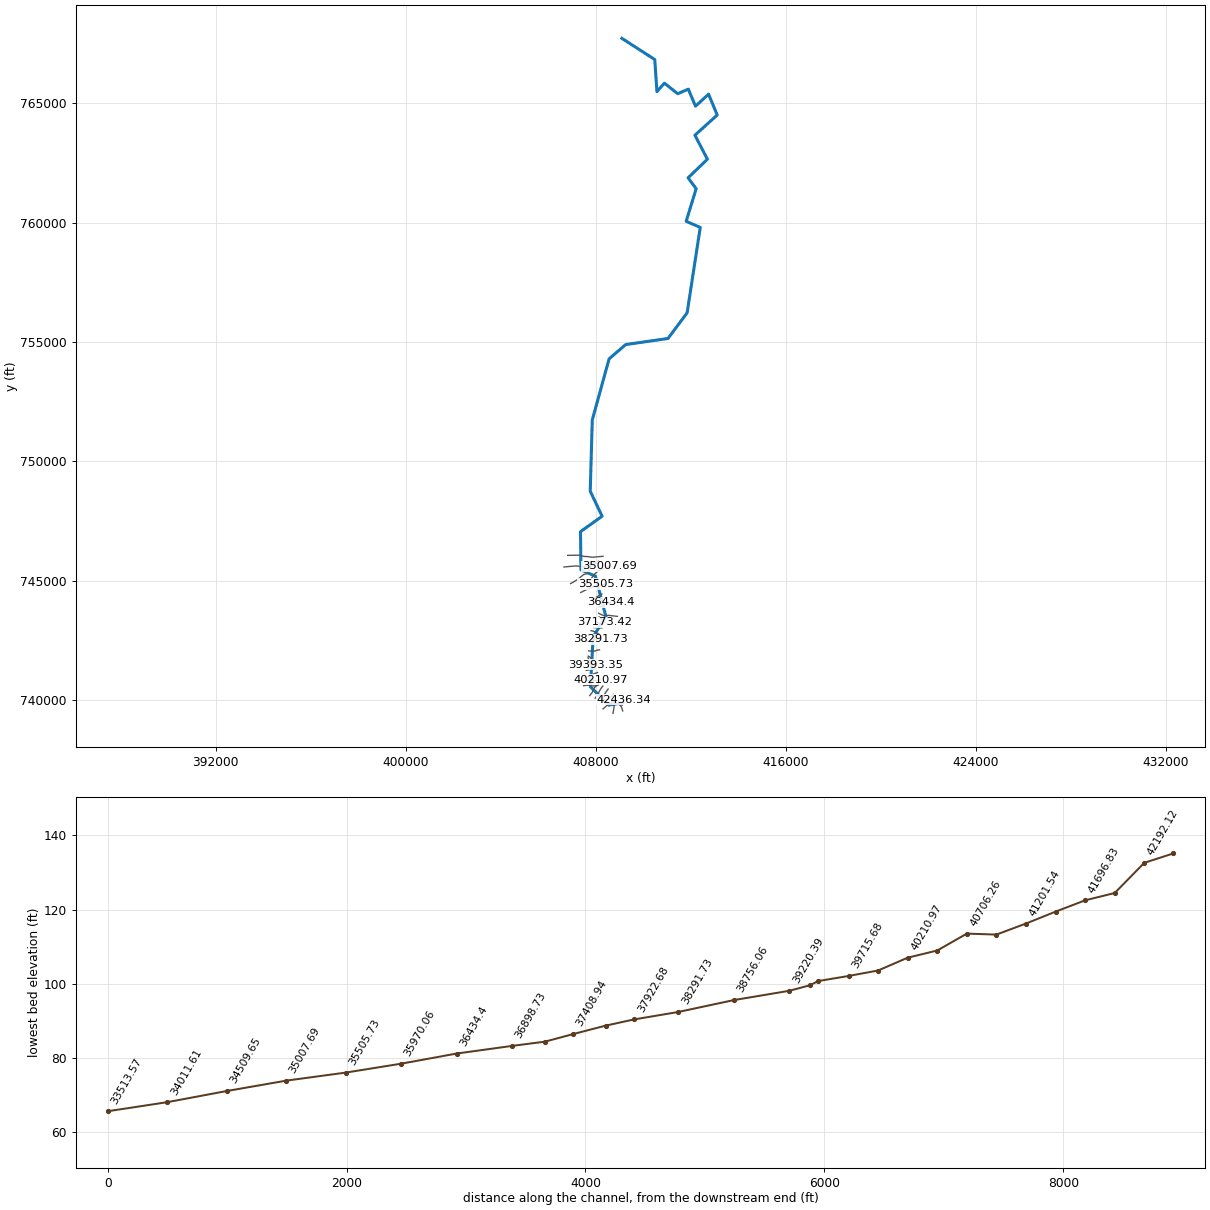
--- 2834_ras.prj (project) ---

Proj Title=2834
Current Plan=p01
Default Exp/Contr=0.3,0.1
English Units
Geom File=g01
Flow File=f01
Plan File=p01
Y Axis Title=Elevation
X Axis Title(PF)=Main Channel Distance
X Axis Title(XS)=Station
BEGIN DESCRIPTION:
RFD model 2834 exported to HEC-RAS
END DESCRIPTION:

--- 2834_ras.p01 (plan) ---

Plan Title=Plan 01
Program Version=4.10
Short Identifier=Plan 01
Geom File=g01
Flow File=f01
Subcritical Flow
Calc Critical at every XS
Secant Critical Depth

--- 2834_ras.f01 (steady flow) ---

Flow Title=Flow 01
Program Version=5.01
Number of Profiles= 6
Profile Names=10yr,25yr,50yr,100yr,100plus,500yr
River Rch & RM=2834,47,42436.34
  887.05 1592.28 2320.57 3071.02 4483.69 6904.34
River Rch & RM=2834,47,42192.12
  910.59 1634.96 2383.23 3154.36 4605.37 7066.86
River Rch & RM=2834,47,41944.48
  911.78 1637.11 2386.39 3158.57 4611.51 7075.07
River Rch & RM=2834,47,41696.83
  943.75 1695.19 2471.77 3272.27 4777.51 7296.37
River Rch & RM=2834,47,41449.19
  947.45  1701.9 2481.63  3285.4 4796.68 7321.82
River Rch & RM=2834,47,41201.54
  962.19 1728.66 2520.97 3337.77 4873.14 7423.29
River Rch & RM=2834,47, 40953.9
  964.19 1732.31 2526.32  3344.9 4883.55 7437.08
River Rch & RM=2834,47,40706.26
  972.86 1748.06 2549.48 3375.74 4928.58 7496.74
River Rch & RM=2834,47,40458.61
   975.2  1752.3 2555.71 3384.04 4940.69 7512.77
River Rch & RM=2834,47,40210.97
  977.19 1755.93 2561.05 3391.14 4951.07  7526.5
River Rch & RM=2834,47,39963.32
  996.51 1790.99 2612.58 3459.75 5051.23 7658.71
River Rch & RM=2834,47,39715.68
  998.99 1795.51 2619.22 3468.59 5064.14 7675.75
River Rch & RM=2834,47,39460.29
 1007.39 1810.79 2641.71 3498.57 5107.91 7733.54
River Rch & RM=2834,47,39393.35
  1009.7 1814.98 2647.88 3506.78  5119.9 7749.38
River Rch & RM=2834,47,39220.39
 1010.03 1815.58 2648.76 3507.96 5121.62 7751.64
River Rch & RM=2834,47,38756.06
 1021.04 1835.62 2678.24 3547.24 5178.98 7827.24
River Rch & RM=2834,47,38291.73
 1029.56 1851.12 2701.06 3577.66 5223.39 7885.72
River Rch & RM=2834,47,37922.68
 1035.45 1861.84 2716.84 3598.69 5254.09  7926.1
River Rch & RM=2834,47,37684.23
 1036.75 1864.22 2720.34 3603.36  5260.9 7935.07
River Rch & RM=2834,47,37408.94
 1039.35 1868.95 2727.32 3612.67  5274.5 7952.98
River Rch & RM=2834,47,37173.42
 1041.14 1872.21 2732.11 3619.07 5283.84 7965.29
River Rch & RM=2834,47,36898.73
 1043.57 1876.64 2738.65 3627.79 5296.57 7982.06
River Rch & RM=2834,47, 36434.4
 1226.14 2206.92 3222.96 4271.09  6235.8 9189.99
River Rch & RM=2834,47,35970.06
 1230.21 2214.34 3233.91 4285.71 6257.14 9217.47
River Rch & RM=2834,47,35505.73
 1257.33 2263.85 3306.94 4383.22  6399.5 9400.53
River Rch & RM=2834,47,35007.69
 1272.65 2291.85 3348.27 4438.43 6480.11 9504.07
River Rch & RM=2834,47,34509.65
 1309.63 2359.42 3448.01 4571.69 6674.67 9753.25
River Rch & RM=2834,47,34011.61
 1315.56  2370.3 3464.09  4593.2 6706.07 9793.51
River Rch & RM=2834,47,33513.57
 1318.91 2376.43 3473.15 4605.33 6723.78 9816.19
River Rch & RM=2834,47,33015.53
  1327.7 2392.54 3496.98 4637.22 6770.34 9875.88
River Rch & RM=2834,47,32517.49
 1337.95 2411.42    3525 4674.83 6825.26 9946.71
River Rch & RM=2834,47,31363.31
 1358.94 2450.05 3582.28 4751.65 6937.4110090.83
River Rch & RM=2834,47,30687.03
 1368.69 2467.95 3608.76 4787.12  6989.2   10157
River Rch & RM=2834,47, 30578.2
 1370.04 2470.42 3612.43 4792.03 6996.3610166.15
River Rch & RM=2834,47,30269.76
 1373.34 2476.47 3621.38 4804.02 7013.87 10188.5
River Rch & RM=2834,47,29554.06
 1384.21 2496.45 3650.98 4843.68 7071.7810262.53
River Rch & RM=2834,47,29149.17
 1680.47 3043.57 4464.16 5936.61 8667.4512284.25
River Rch & RM=2834,47,28999.36
 1681.17 3044.86 4466.08  5939.2 8671.2312288.96
River Rch & RM=2834,47,28727.92
 1683.42 3049.01 4472.24 5947.48 8683.3212304.05
River Rch & RM=2834,47,28076.41
  1689.3 3059.87 4488.39 5969.19 8715.0112343.63
River Rch & RM=2834,47, 27234.3
 1707.48 3093.52 4538.49  6036.6 8813.4312466.76
River Rch & RM=2834,47,27073.59
 1720.51 3117.77 4574.72 6085.51 8884.8512556.69
River Rch & RM=2834,47,25445.19
 1732.56 3140.14 4608.07 6130.46 8950.48 12638.9
River Rch & RM=2834,47,24052.19
  1787.5 3242.12 4760.16 6335.47 9249.7813012.75
River Rch & RM=2834,47,22333.67
 2371.63 4329.75  6385.8  8530.512454.54 16934.1
River Rch & RM=2834,47, 21266.2
 2624.26 4793.59 7073.05 9450.9313798.3618499.83
River Rch & RM=2834,47,20333.89
 2644.93  4831.2 7128.45 9524.7213906.0918622.59
Boundary for River Rch & Prof#=2834,47,1
Up Type= 0
Dn Type= 2
Boundary for River Rch & Prof#=2834,47,2
Up Type= 0
Dn Type= 2
Boundary for River Rch & Prof#=2834,47,2
Up Type= 0
Dn Type= 2
Boundary for River Rch & Prof#=2834,47,2
Up Type= 0
Dn Type= 2
Boundary for River Rch & Prof#=2834,47,2
Up Type= 0
Dn Type= 2
Boundary for River Rch & Prof#=2834,47,2
Up Type= 0
Dn Type= 2

--- 2834_ras.g01 (geometry) ---

Geom Title=2834
Program Version=4.10

River Reach=2834,47
Reach XY= 30
409141.495036066739881.997597948408555.865585893739777.669347018
407775.865585893740547.113791451407892.115585893742647.947124794
408426.837808043743492.391569287407985.350539535745184.555921078
407377.017206192745447.333698884407359.239428431747050.667032212
408267.572761774747696.222587764407768.267206222748746.222587794
407853.857484192 751731.36147666408563.301928431754295.250365496
409261.635262281754891.500365674411041.635261834755148.167032272
411846.149150938756222.472587809412398.426928699759803.722587779
411805.579706192 760059.76425454412226.993759602761426.143164143
411886.621372879 761882.61147666412700.866107494762661.741139144
 412174.47731626763667.990968511 413113.09156087 764515.85456723
412748.751283348765388.042068124412198.334616542764885.125401124
411897.084616452 765599.43095611411450.973505318765408.875400618
 410888.51677528765850.467920631410575.950357169765493.296696931
410484.283690751766839.963363752409099.839246362767729.407807991

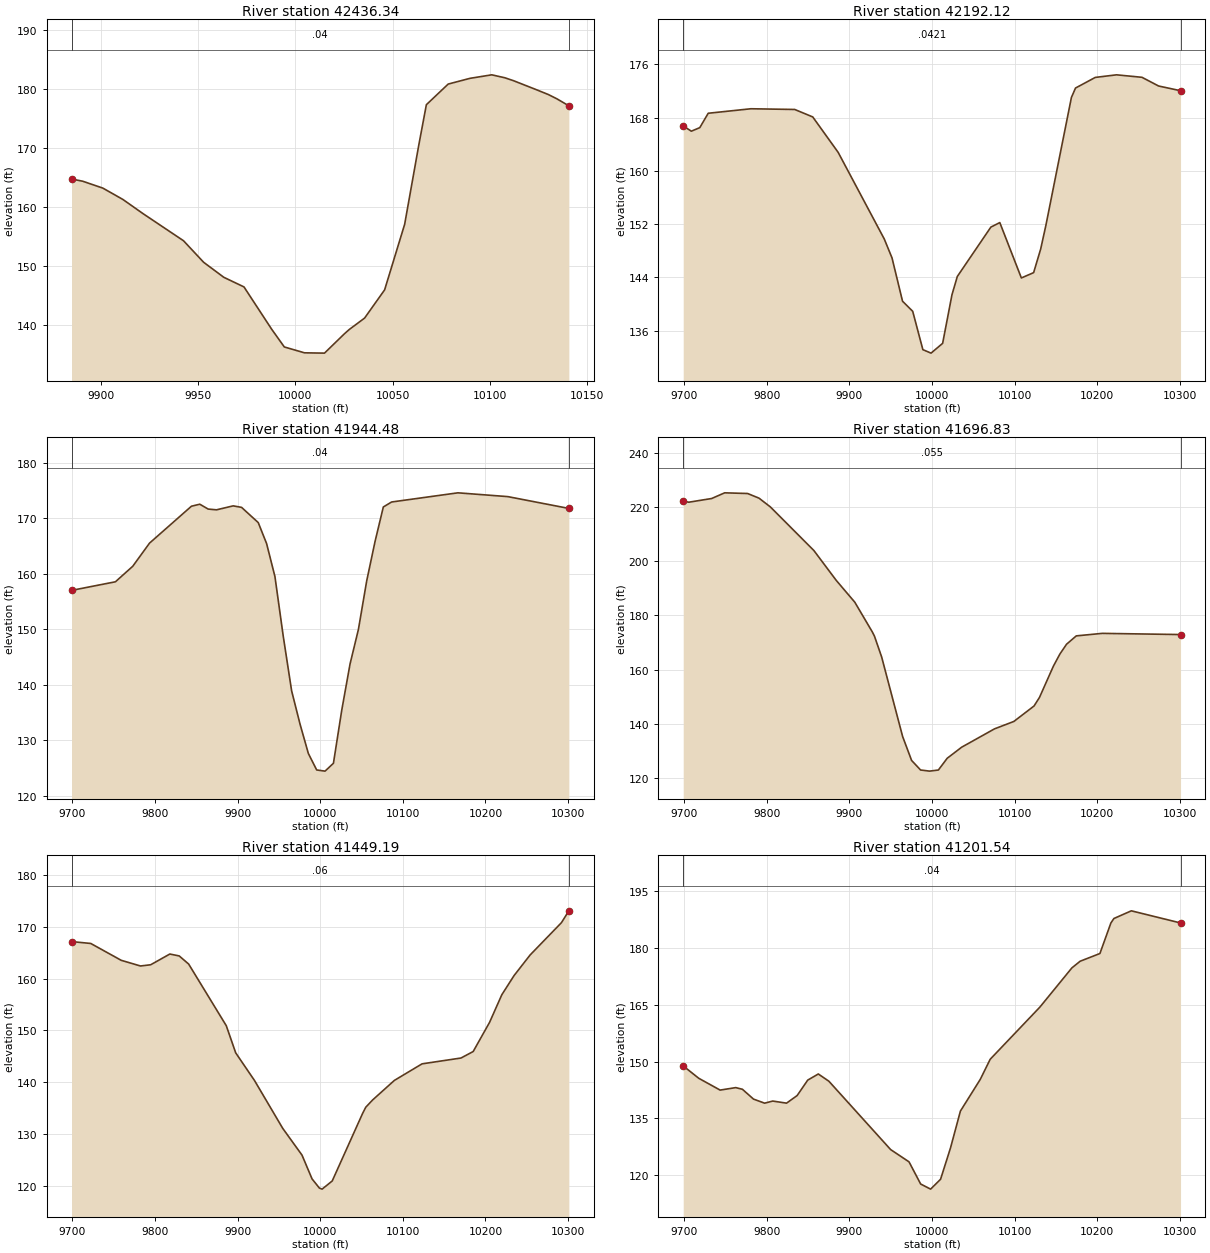
Type RM Length L Ch R = 1 ,42436.34,244.215800,244.215800,244.215800
XS GIS Cut Line= 5
409107.773166448739769.477281407409139.399529159739884.754250035
409152.007447779739935.614947855409168.884277523739968.782836974
409189.717610866740010.449503645
#Sta/Elev= 29
 9884.94164.68289890.666164.31099901.036163.14279911.406161.20669921.775158.7965
9942.514154.21859952.884150.55959963.253148.01519973.623146.38649987.848 139.217
9994.362136.204610004.73135.209910015.03135.158110025.33138.457310027.75139.1638
10035.64141.098710045.94145.885910056.24156.999310063.48170.377210067.41177.2845
10078.63180.784710089.85181.756810101.04 182.35210107.77181.850910112.22181.3581
 10123.4179.906310130.13179.011110134.58178.275110140.68177.0942
#Mann= 3 , 0 , 0
 9884.94    0.04       0 9884.94    0.04       010140.68    0.04       0
#XS Ineff= 2 , 0
       0                               0
Bank Sta=9884.94,10140.68
Exp/Cntr=0.3,0.1

Type RM Length L Ch R = 1 ,42192.12,247.644100,247.644100,247.644100
XS GIS Cut Line= 6
409136.535733656739535.371849305 409077.06618351739712.111438885
409032.358411845739764.095625834408883.059413207739871.765973127
408844.895276765739947.623014686 408836.02628058740021.526543297
#Sta/Elev= 30
9699.155166.73789708.983165.94489719.189166.47749729.396 168.6399781.051169.3142
9834.071169.20799855.873168.08589886.641 162.7629942.433149.7487 9951.76146.9239
9964.504140.41219976.806138.89679989.107133.1387    9999132.616610013.02134.0852
10024.31141.379110030.78144.126310071.37151.540710082.19152.221810108.28143.9038
10123.12144.704710131.67148.260710137.95151.811510168.83171.009910173.78172.4227
10197.69174.020810223.39174.410510254.18174.038310274.33172.731410300.87172.0238
#Mann= 3 , 0 , 0
9699.155  0.0421       09699.155  0.0421       010300.87  0.0421       0
#XS Ineff= 2 , 0
       0                               0
Bank Sta=9699.155,10300.87
Exp/Cntr=0.3,0.1

Type RM Length L Ch R = 1 ,41944.48,247.644000,247.644000,247.644000
XS GIS Cut Line= 6
 408725.23165813739432.174673163408747.392097957 739550.62516969
408776.750934794 739748.83316801408782.654728574739801.385719347
408793.275154677739933.987418663408810.237888782740027.585348297
#Sta/Elev= 30
9699.024156.99819752.143158.54739773.113161.3372 9793.46165.50699844.163172.1444
9854.269172.50559864.375171.63219874.481171.49489894.693172.20779904.799171.9413
9925.011169.20069935.116165.43099945.222159.49119955.328148.70199965.434138.9154
 9975.54132.97399985.646127.66519995.752124.686410005.88124.480610016.02 125.892
10026.11 135.46410036.17143.786710046.24149.9562 10056.3  158.7210066.36165.7766
10076.41172.006610086.45172.9053 10166.7174.554310227.07173.872310300.97171.7472
#Mann= 3 , 0 , 0
9699.024    0.04       09699.024    0.04       010300.97    0.04       0
#XS Ineff= 2 , 0
       0                               0
Bank Sta=9699.024,10300.97
Exp/Cntr=0.3,0.1

Type RM Length L Ch R = 1 ,41696.83,247.644100,247.644100,247.644100
XS GIS Cut Line= 6
408310.306480409739620.124804785408457.737891152739753.186669766
408593.047405057739821.464477272408680.151263629739879.625651207
408730.886920079 739929.75089388408771.730370602 739992.11206589
#Sta/Elev= 30
9699.065 222.1499705.853221.74419733.501223.10819749.236225.20499776.975224.9536
9790.767223.2411 9804.56219.99429857.187203.90959884.344192.85629906.699184.8446
9927.825 173.9099930.455 172.3429939.221164.60789964.561135.29689975.423126.4552
9986.285122.92279997.147122.505610007.86122.916710018.55127.258710036.05131.3405
10075.75138.101710099.19 140.83910123.62146.544610130.18149.699210147.05161.2579
10154.85165.692410162.94169.327210174.72 172.41410206.13173.3428 10300.9172.9049
#Mann= 3 , 0 , 0
9699.065   0.055       09699.065   0.055       0 10300.9   0.055       0
#XS Ineff= 2 , 0
       0                               0
Bank Sta=9699.065,10300.9
Exp/Cntr=0.3,0.1

Type RM Length L Ch R = 1 ,41449.19,247.644000,247.644000,247.644000
XS GIS Cut Line= 6
408266.188758803739877.301382242408353.642377839739937.203607089
408497.206204919740015.317907549408609.558309636740094.303700491
408685.272309679740158.730925238408746.395435231740232.075278612
#Sta/Elev= 30
9699.071167.11839722.342166.75519759.205163.51029782.523162.4187 9794.85162.6516
9818.049164.72099829.434164.35049840.818162.79069886.356150.9179 9897.74145.6959
9920.509140.36869954.662131.15499978.009125.99619990.135121.4258    9999119.6571
10002.32119.448310014.57  121.0210051.32134.018110055.16135.218310063.57136.6326
10089.79140.384610123.28143.5727 10170.4144.694310185.15145.943210205.03151.5724
10219.84156.884810234.68160.578410254.07164.5364   10292170.764610300.95173.0398
#Mann= 3 , 0 , 0
9699.071    0.06       09699.071    0.06       010300.95    0.06       0
#XS Ineff= 2 , 0
       0                               0
Bank Sta=9699.071,10300.95
Exp/Cntr=0.3,0.1

Type RM Length L Ch R = 1 ,41201.54,247.644100,247.644100,247.644100
XS GIS Cut Line= 6
408162.425471658739971.827570096408240.555265559740058.431416328
408295.453990667 740126.92064232408327.238942464740171.840998865
408436.376110155 740335.14799604408522.618711801740453.061577522
#Sta/Elev= 30
9699.031148.84189717.803145.57719743.708142.45039762.589143.10599770.644142.6697
9784.112140.0645 9797.58138.98799807.376  139.559824.087138.99439836.904 141.001
 9849.72 145.0879862.536146.70679875.352144.79439950.093126.70869972.349123.4599
9986.412117.60129998.475116.247310010.51118.855610022.53127.139610034.54136.8979
10058.58145.288710070.59150.607710130.68164.3934 10169.5174.789810179.49176.5441
10203.38178.581910216.66186.653210220.32187.847210241.43189.878210300.98186.6684
#Mann= 3 , 0 , 0
9699.031    0.04       09699.031    0.04       010300.98    0.04       0
#XS Ineff= 2 , 0
       0                               0
Bank Sta=9699.031,10300.98
Exp/Cntr=0.3,0.1

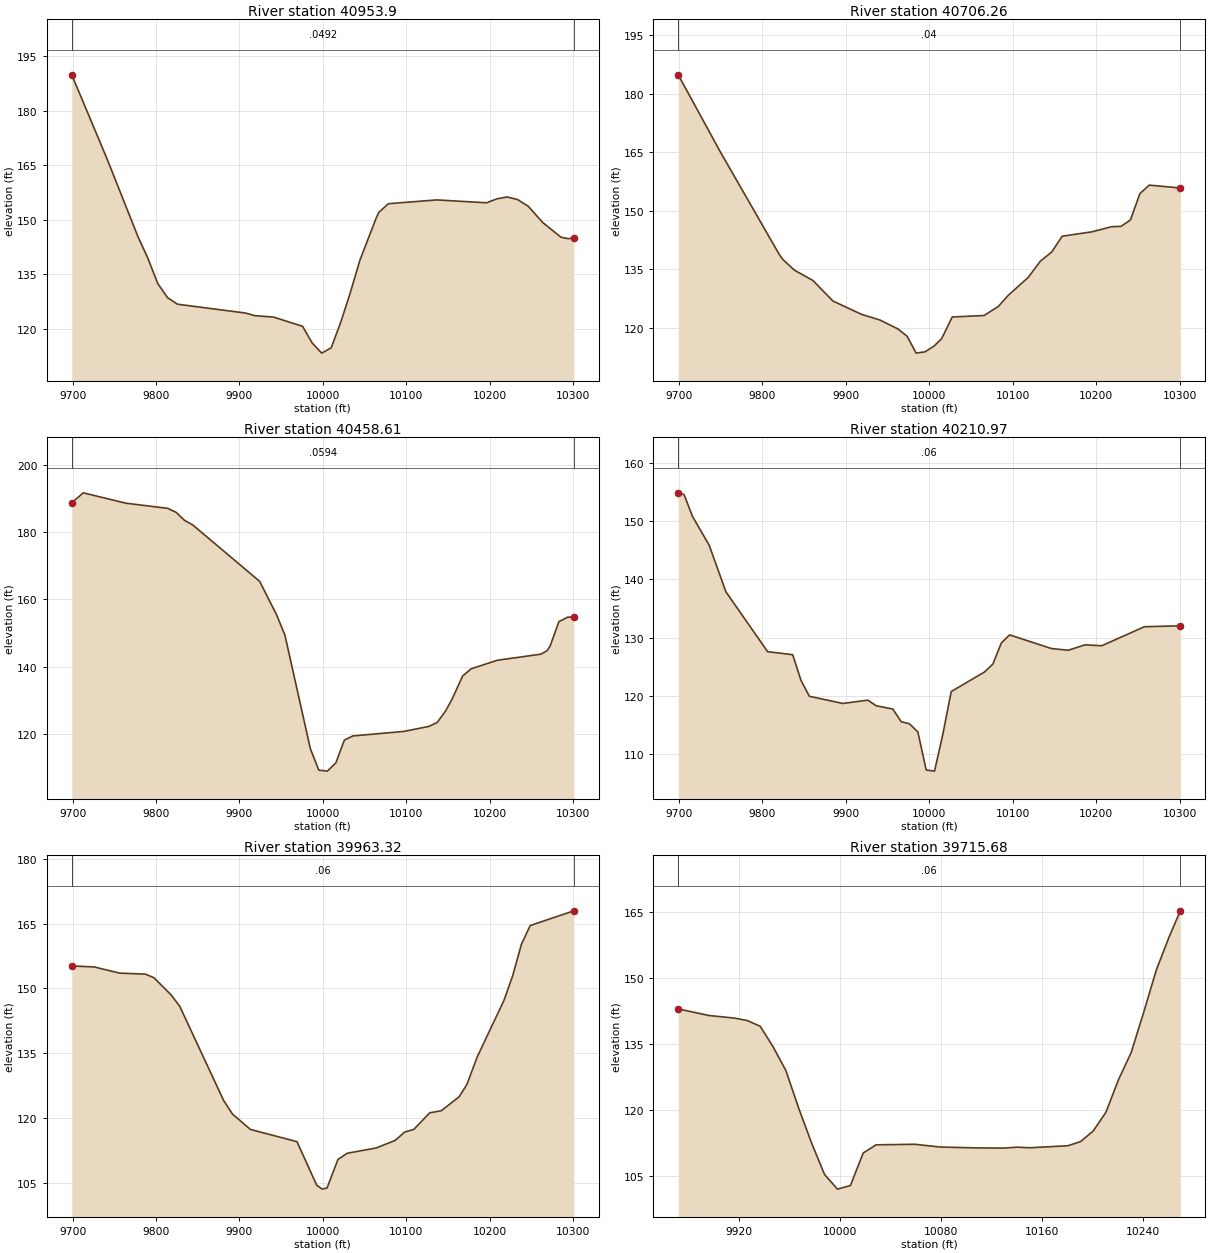
Type RM Length L Ch R = 1 , 40953.9,247.644100,247.644100,247.644100
XS GIS Cut Line= 6
407976.173161315740070.229197755408017.891935285740128.593506075
408060.910857391740196.062072337408210.470906483740460.828531173
408251.095576478740519.549171878408299.039300089740576.770634138
#Sta/Elev= 30
9699.027189.87629741.767166.48539778.366145.33399790.226139.42139802.086132.4337
9813.946 128.5249825.806126.72969906.915124.31429918.385123.57999940.809123.1925
9975.733120.65359987.203116.07239998.673113.2635 10010.1114.746710021.52121.7878
10032.94129.889310044.36138.7725 10064.2150.5738 10067.2152.037310078.62154.3968
10136.47  155.4410196.45154.649510208.61155.733410220.77156.258410233.41155.5535
10246.45153.662910263.52149.236710285.59145.168210294.66 144.76410300.95145.0251
#Mann= 3 , 0 , 0
9699.027  0.0492       09699.027  0.0492       010300.95  0.0492       0
#XS Ineff= 2 , 0
       0                               0
Bank Sta=9699.027,10300.95
Exp/Cntr=0.3,0.1

Type RM Length L Ch R = 1 ,40706.26,247.644000,247.644000,247.644000
XS GIS Cut Line= 6
407749.191420698740177.114646216 407856.56468334740318.288723461
 407932.39858372740485.309084639407956.362076367 740524.21743802
408003.586376503740567.307045475408118.079783023740630.199691164
#Sta/Elev= 30
 9699.06184.84429749.214165.21419820.298138.7687 9824.42137.53459838.156134.8181
9860.629132.12299884.369 126.8999918.573123.48329940.836122.01279962.636119.7035
 9973.45  117.859984.264113.52919995.078113.879510005.87 115.37510014.78117.2346
10027.52122.792910065.66123.167410082.86125.518410094.77128.3654 10118.6132.9318
10133.11 137.09110146.73139.437610159.35143.4928 10195.1144.618210218.36145.9174
10229.87 146.01410241.13147.654710252.38154.388610263.64156.583410300.88155.8427
#Mann= 3 , 0 , 0
 9699.06    0.04       0 9699.06    0.04       010300.88    0.04       0
#XS Ineff= 2 , 0
       0                10047.91       0
Bank Sta=9699.06,10300.88
Exp/Cntr=0.3,0.1

Type RM Length L Ch R = 1 ,40458.61,247.644100,247.644100,247.644100
XS GIS Cut Line= 6
407491.405515746740592.075131439407585.988253917740607.982318364
407676.128634193740611.942486519407904.512049249740578.643017901
407974.064663003740589.978643666408081.766202069740626.417305816
#Sta/Elev= 30
9699.042188.72829712.877191.66039763.709188.58639814.057187.05079824.089 185.877
9834.122183.49319844.142182.10419924.244 165.3619944.437155.48489954.534149.4029
9985.017115.64119995.184109.251110005.37108.9676 10015.6111.417910025.82 118.207
10036.04119.426310097.02120.762510127.11122.251610137.18123.443510147.24126.8964
 10154.8130.293910167.59137.232810177.83139.3758   10209141.901810261.55143.7309
10268.65144.738710272.25146.019710282.94153.377810293.64154.728410300.87154.6798
#Mann= 3 , 0 , 0
9699.042  0.0594       09699.042  0.0594       010300.87  0.0594       0
#XS Ineff= 2 , 0
       0                10073.03       0
Bank Sta=9699.042,10300.87
Exp/Cntr=0.3,0.1

Type RM Length L Ch R = 1 ,40210.97,247.644000,247.644000,247.644000
XS GIS Cut Line= 6
 407597.97414271740808.995632647407723.328266154740814.601419405
407943.106655151740807.444786871408021.924701421740808.172637939
408115.552047118740819.212509551408196.577353025740838.743371422
#Sta/Elev= 30
9699.028154.88599706.069154.57799716.091150.83529736.135145.88049756.179137.8706
9806.206127.57249836.217127.05429846.223122.63819856.229119.90619896.253118.6707
9926.271119.23729936.277118.27869956.289117.70799966.295115.53979976.301115.1686
9986.307113.77059996.313107.226910006.32107.034310016.32113.407810026.32120.7189
10066.33124.088810076.33125.454210086.33129.051310096.33  130.46 10146.4 128.116
10166.49127.8153 10186.7128.744210206.92 128.59710257.94131.864510300.96132.0185
#Mann= 3 , 0 , 0
9699.028    0.06       09699.028    0.06       010300.96    0.06       0
#XS Ineff= 2 , 0
       0                10077.06       0
Bank Sta=9699.028,10300.96
Exp/Cntr=0.3,0.1

Type RM Length L Ch R = 1 ,39963.32,247.644100,247.644100,247.644100
XS GIS Cut Line= 6
407518.786896757740927.371596399407621.167465151740949.637177215
407707.861652981740976.672351534 407765.90941604741003.092167408
407912.192288026741088.482995687408075.440798311741144.484107097
#Sta/Elev= 30
9699.049155.21249725.875154.97739756.576153.53899787.277153.32259797.511152.4896
9818.186148.50029828.569145.84519881.072124.10719891.647 120.9589913.245117.3871
9969.049114.55719992.762 104.4549999.368103.578410005.08103.841910018.18110.4504
10029.19111.872610064.08113.101910086.89114.862710098.01116.7621 10109.1117.3925
10128.17121.227410141.96121.704610163.49 124.94510172.75127.796210185.03134.1284
10217.06147.193210227.58152.9041 10238.1160.232510248.62164.552310300.95167.9581
#Mann= 3 , 0 , 0
9699.049    0.06       09699.049    0.06       010300.95    0.06       0
#XS Ineff= 2 , 0
       0                10105.38       0
Bank Sta=9699.049,10300.95
Exp/Cntr=0.3,0.1

Type RM Length L Ch R = 1 ,39715.68,255.386700,255.386700,255.386700
XS GIS Cut Line= 6
407600.999583873741236.306847883407657.732716377741245.357154123
407805.304733595741275.129139367407879.474685233741285.643338712
407950.668866241741291.268367167407993.840807248741292.593686759
#Sta/Elev= 30
9871.973142.98779896.277141.49919916.529140.90739926.656140.34969936.838139.0593
 9947.04 134.4299957.243128.98019967.446120.38669977.648112.49119987.851105.4166
9998.054102.104810008.26102.912210018.46110.311610028.66112.157410059.26112.2796
10079.66111.647910109.96111.451510130.16111.420710140.26111.624810150.36 111.492
10180.48111.946510190.52112.895410200.55115.304910210.58 119.53610220.61126.9708
10230.63133.122710240.63142.346110250.64151.941710260.64159.324410269.49165.2463
#Mann= 3 , 0 , 0
9871.973    0.06       09871.973    0.06       010269.49    0.06       0
#XS Ineff= 2 , 0
       0                10101.89       0
Bank Sta=9871.973,10269.49
Exp/Cntr=0.3,0.1

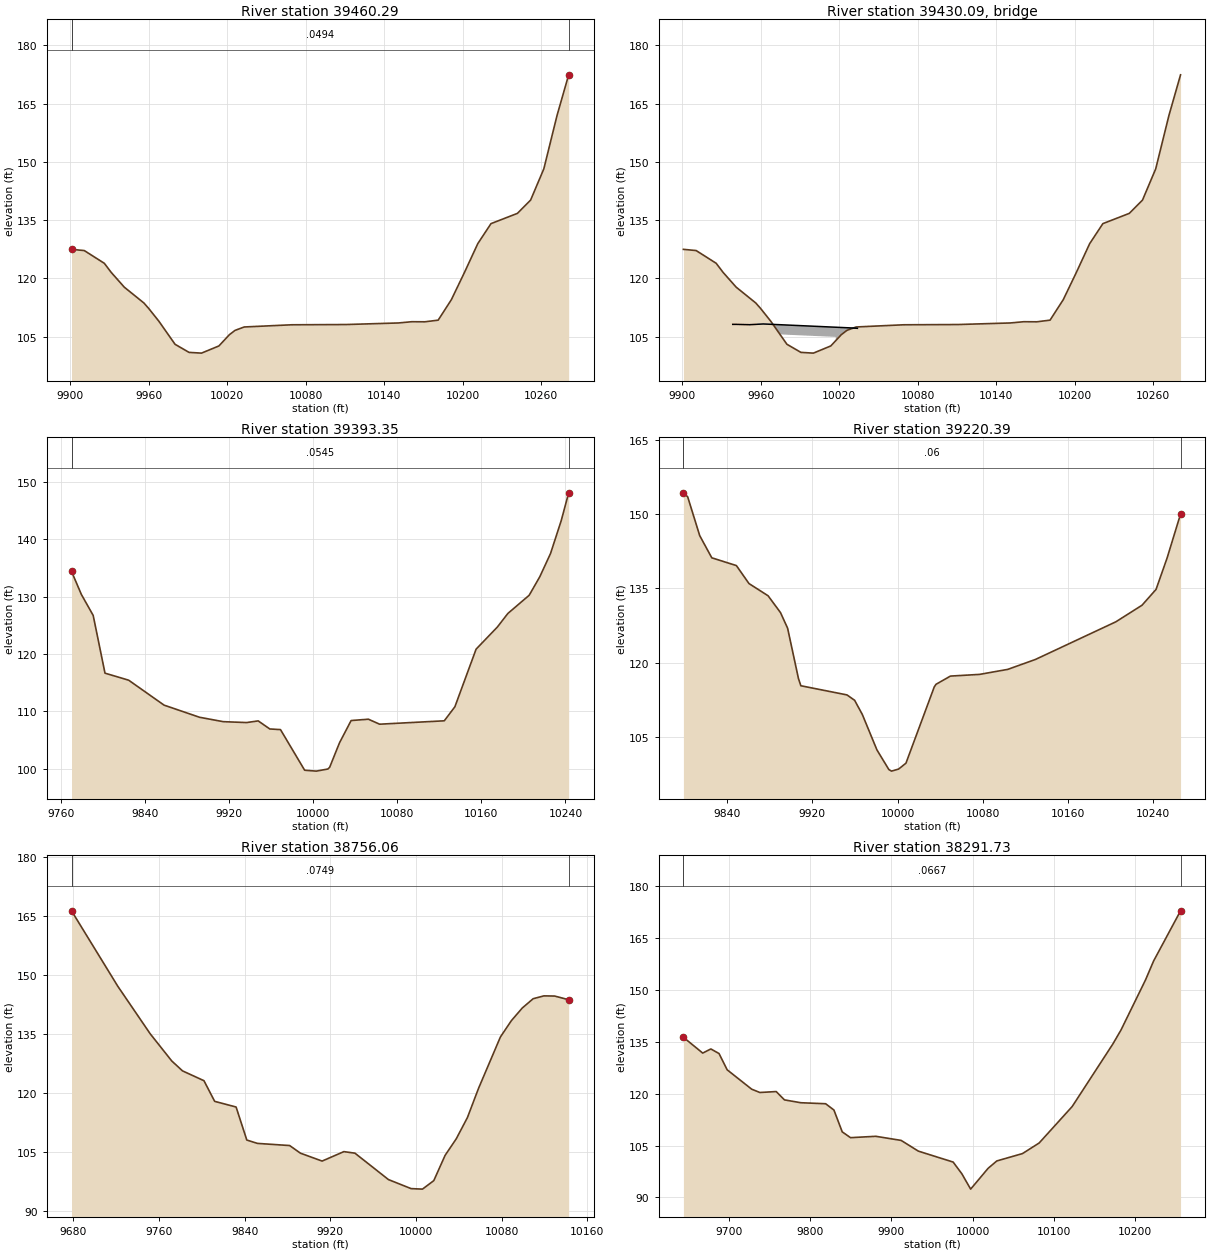
Type RM Length L Ch R = 1 ,39460.29,66.940800,66.940800,66.940800
XS GIS Cut Line= 6
407678.624506027741587.984704047407708.319239736741553.588002652
407744.730631679741488.118774489407778.584798366741464.681274489
407810.702853918741455.132663369407993.660103053741428.511106551
#Sta/Elev= 30
 9900.89127.45839910.646127.14639925.949123.86739931.255121.51479941.252117.7136
9956.214113.64679959.833112.26429967.722108.92629980.042103.00719990.737100.9203
10000.25100.729210013.57102.577110021.62105.483510025.92106.589110032.94107.4636
10069.26108.027910110.51108.092710150.91108.498810161.01108.816510171.11108.7999
10181.21109.220110191.31114.4971 10201.4121.5681 10211.5128.9209 10221.6134.0821
 10241.8136.7238 10251.9140.1481   10262148.195610272.12161.965310280.99172.4075
#Mann= 3 , 0 , 0
 9900.89  0.0494       0 9900.89  0.0494       010280.99  0.0494       0
#XS Ineff= 2 , 0
       09958.148        10067.57       0
Bank Sta=9900.89,10280.99
Exp/Cntr=0.3,0.1

Type RM Length L Ch R = 3 ,39430.09,,,
BEGIN DESCRIPTION:
END DESCRIPTION:
Bridge Culvert--1,0,-1,-1, 0
Deck Dist Width WeirC Skew NumUp NumDn MinLoCord MaxHiCord MaxSubmerge Is_Ogee
22.220400,22.500000,2.6,0, 11, 11, , , 0.95, 0, 0,0,,
 9938.60 9940.90 9951.45 9962.00 9963.28 9974.69 9974.6910017.3910017.3910029.79
10033.91
  108.14  108.14  108.05  108.24  108.22  108.05  108.05  107.40  107.40  107.21
  107.12
 -891.86 -891.86 -891.95 -891.76 -891.78 -891.95  105.55  104.90 -892.60 -892.79
 -892.88
 9938.60 9940.90 9951.45 9962.00 9963.28 9978.77 9978.7710021.4710021.4710029.79
10033.91
  108.14  108.14  108.05  108.24  108.22  107.99  107.99  107.34  107.34  107.21
  107.12
 -891.86 -891.86 -891.95 -891.76 -891.78 -892.01  105.49  104.84 -892.66 -892.79
 -892.88
BR Coef=-1 , 0 , 0 ,, 0 ,,,0.8,0,1,0,
WSPro=,,,, 1 ,,,, 0 ,,,, 0 ,,,,-1 ,-1 ,-1 , 0 , 0 , 0 , 0 , 0
BC Design=,, 0 ,, 0 ,,,,,,

Type RM Length L Ch R = 1 ,39393.35,172.960700,172.960700,172.960700
XS GIS Cut Line= 6
407675.152283698741763.331926286407746.332839251741625.311092928
407795.993491739 741520.19604528407802.022298366741515.028496698
407831.536187261741503.743774489407991.992561489  741479.4777596
#Sta/Elev= 30
9769.703  134.399779.078130.3721 9790.33126.72199801.581116.66459824.084115.4458
9857.839111.09779891.593108.98679914.096 108.2219936.402108.06299947.462108.3525
9958.522106.94749968.698106.83639991.70199.7633810002.7699.6066710013.8299.97439
10015.52100.283510024.88104.533610035.94108.415310052.38108.648710063.09107.7787
10124.67108.369110134.77110.818110154.96120.847410175.15124.686610185.24127.0686
10205.49130.228210215.66133.474610225.83137.5009   10236143.2206 10243.1148.0678
#Mann= 3 , 0 , 0
9769.703  0.0545       09769.703  0.0545       0 10243.1  0.0545       0
#XS Ineff= 2 , 0
       09944.444        10054.02       0
Bank Sta=9769.703,10243.1
Exp/Cntr=0.3,0.1

Type RM Length L Ch R = 1 ,39220.39,464.332600,464.332600,464.332600
XS GIS Cut Line= 6
407681.356393833741831.672400654 407716.41678462741813.170836706
407774.391516423741774.141771402 407902.88991255741649.049578309
407963.005206221741599.152836862408045.994689886741543.490859339
#Sta/Elev= 30
 9798.75154.31219802.767153.5057 9814.07145.66999825.431141.18789848.546139.6203
9860.365135.99089878.344133.52119889.976130.13369896.685126.97089906.882116.8107
9909.142 115.3549952.515113.49919959.685112.41339966.915109.54999980.633102.3977
9991.83898.432379994.35198.11183   1000198.5298510007.9199.7179110034.49115.1027
10036.15115.642610049.71117.304710077.09 117.64610103.59118.658810129.58120.6597
10205.26128.272410229.82131.620710242.98134.8131 10253.3141.1171   10266150.0264
#Mann= 3 , 0 , 0
 9798.75    0.06       0 9798.75    0.06       0   10266    0.06       0
#XS Ineff= 2 , 0
       09942.342                       0
Bank Sta=9798.75,10266
Exp/Cntr=0.3,0.1

Type RM Length L Ch R = 1 ,38756.06,464.332600,464.332600,464.332600
XS GIS Cut Line= 6
407702.141819298742052.425917223407817.238494724742038.507208526
407906.357855946742038.305551678407983.475310504 742053.61594075
408076.720948696742084.208720416408157.939543813742097.693175763
#Sta/Elev= 30
9678.264166.39619721.519147.19989751.797135.11079771.887128.21339781.931125.6914
 9801.99123.18699811.997117.93449832.011116.49449842.018108.09149852.026107.2381
9882.056106.6921 9892.15104.74919912.366102.74289932.706105.1472 9943.05104.7527
9974.35898.036339995.52695.7381910006.1295.60804 10016.7 97.766610027.29104.2076
10037.72108.420410048.13113.814510058.53 121.25810078.97134.323610089.17138.4569
10099.37141.674210109.52144.0376 10119.6144.765710129.67144.716510142.71143.7776
#Mann= 3 , 0 , 0
9678.264  0.0749       09678.264  0.0749       010142.71  0.0749       0
#XS Ineff= 2 , 0
       09902.181                       0
Bank Sta=9678.264,10142.71
Exp/Cntr=0.3,0.1

Type RM Length L Ch R = 1 ,38291.73,369.043900,369.043900,369.043900
XS GIS Cut Line= 6
407601.286801487742445.146474034407712.391630441742453.896737635
407809.621028364742470.973450124408039.452555954742545.769868359
408129.808100849742551.126052514408198.051975518742546.260066718
#Sta/Elev= 30
9644.238136.24549667.977131.68759677.988  132.889688.012131.56289698.059126.8569
9728.199121.26049738.245120.30739758.356120.5784 9768.47 118.1769788.698117.3505
9819.116117.06189829.328115.2463 9839.54108.93719849.752107.26369880.777107.6614
 9911.99106.47319933.154103.37559975.916100.22299986.67996.824889997.443 92.4059
10018.9398.4154510029.64100.543810061.19102.670910081.71105.730110122.29116.2525
10172.34134.320410182.35138.360910212.41152.772310222.44158.282710255.57172.7641
#Mann= 3 , 0 , 0
9644.238  0.0667       09644.238  0.0667       010255.57  0.0667       0
#XS Ineff= 2 , 0
       09922.112                       0
Bank Sta=9644.238,10255.57
Exp/Cntr=0.3,0.1

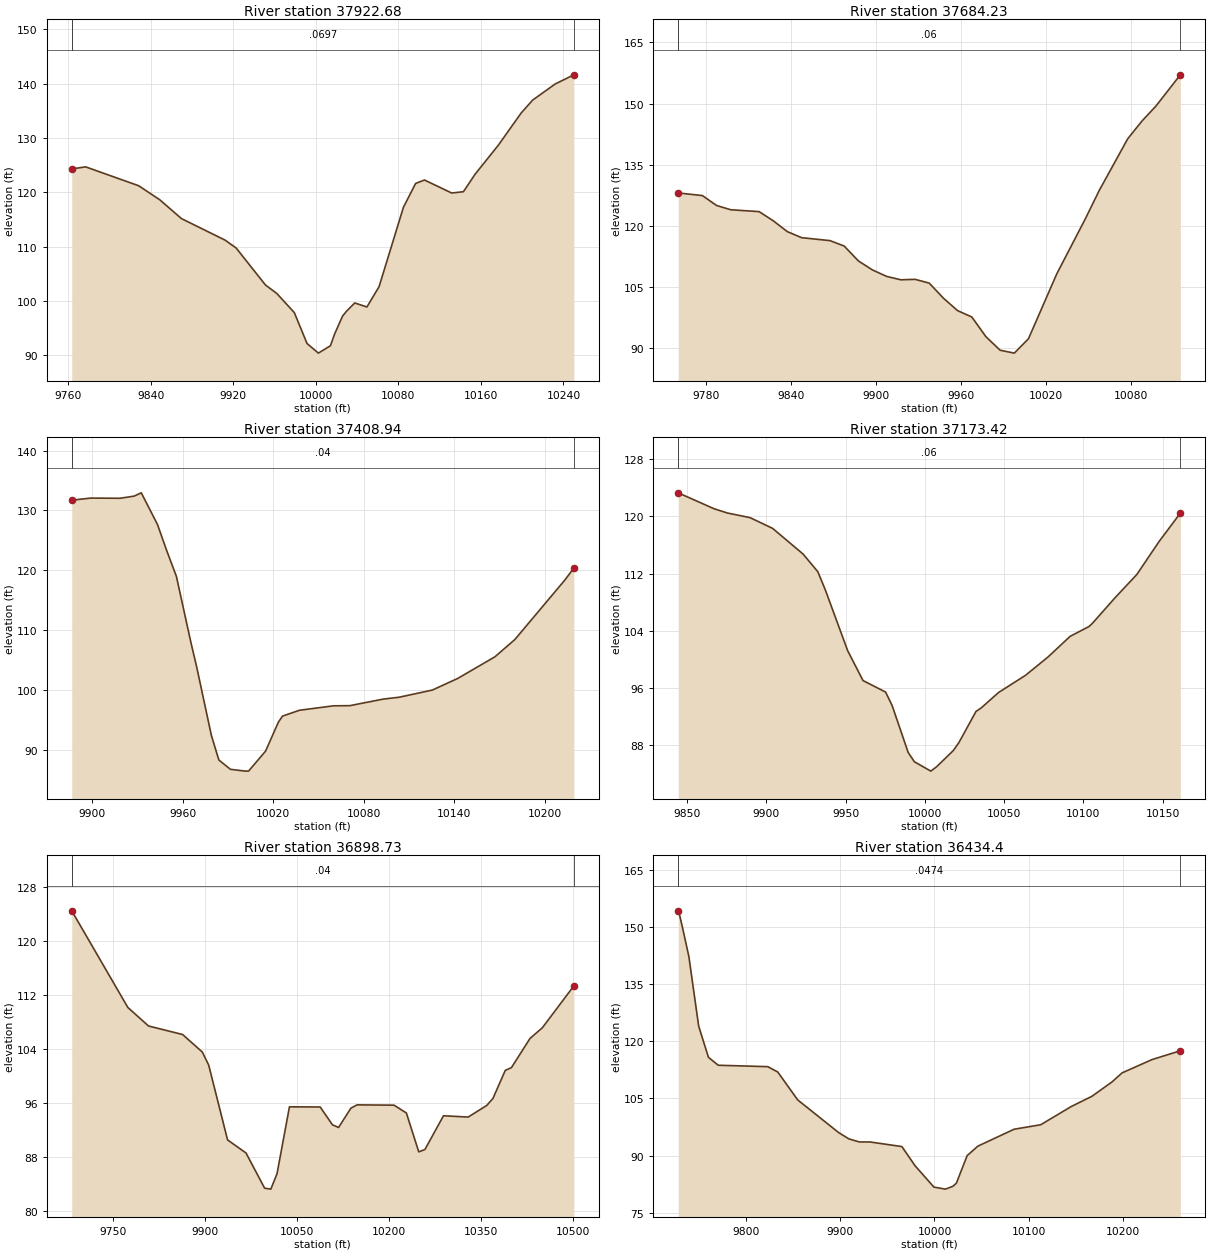
Type RM Length L Ch R = 1 ,37922.68,238.448200,238.448200,238.448200
XS GIS Cut Line= 6
407801.972654919742900.826322829407884.334291557742881.242037018
407960.978115271742854.755591651407990.471008907742840.124832024
408126.309050481742756.232755651408241.625653009742700.337212985
#Sta/Elev= 30
9763.491124.31439776.881 124.7059828.275121.23019848.847118.63289869.812115.1739
9912.066111.21399922.851109.75259951.251102.94419962.221101.3867 9979.18 97.8685
9991.545 92.169910002.5390.40129 10014.291.7638210018.1593.8723910025.9897.23251
10029.9298.1424810037.7799.6395710049.5798.9001110061.36102.650110084.95117.2593
10096.75121.641710105.35122.280210131.75119.8842 10143.1 120.12810154.46123.3584
10176.96128.698110199.14134.638810210.23136.998810232.07139.966910250.12141.6505
#Mann= 3 , 0 , 0
9763.491  0.0697       09763.491  0.0697       010250.12  0.0697       0
#XS Ineff= 2 , 0
       0                               0
Bank Sta=9763.491,10250.12
Exp/Cntr=0.3,0.1

Type RM Length L Ch R = 1 ,37684.23,275.298300,275.298300,275.298300
XS GIS Cut Line= 2
407907.939543724743030.610093921408262.106210411743014.985093921
#Sta/Elev= 30
 9760.08128.05179777.157127.40339787.167124.96829797.177123.92449817.196123.4646
9827.206121.20489837.216118.53559847.225117.07219867.245116.34499877.255115.0206
9887.264111.37019897.274109.13979907.284107.55679917.294106.72979927.303106.8432
9937.313105.91389947.323102.22149957.33299.160179967.34297.609549977.35292.75678
9987.36289.440229997.37188.7283610007.3892.26197 10027.4108.210810047.42121.6234
10057.43128.714410077.45141.344310087.46 145.67710097.47149.417510114.59157.0479
#Mann= 3 , 0 , 0
 9760.08    0.06       0 9760.08    0.06       010114.59    0.06       0
#XS Ineff= 2 , 0
       0                               0
Bank Sta=9760.08,10114.59
Exp/Cntr=0.3,0.1

Type RM Length L Ch R = 1 ,37408.94,235.511100,235.511100,235.511100
XS GIS Cut Line= 6
407967.522263139743350.626484558408013.380713791743289.061005563
408028.426499486743275.246623039 408043.07943958743265.057711899
408092.261319935743239.650546938408240.404768229743173.066113621
#Sta/Elev= 30
 9886.43131.70079898.933132.05089918.406132.02079927.747132.38029932.514132.9304
9943.296127.61799949.209123.38429955.784118.97469965.399107.93639969.206103.8664
9978.97592.412219983.62788.539499984.05988.260179991.63386.72924 10001.6  86.429
10003.6486.4401210014.8989.7651310023.3994.6035110026.1595.62387 10037.496.59886
10059.8397.3391110070.7797.3674310092.6598.4520610103.5998.7842610125.4799.97455
10142.29101.915110166.95 105.53310180.16108.416410213.29118.356410219.26120.3571
#Mann= 3 , 0 , 0
 9886.43    0.04       0 9886.43    0.04       010219.26    0.04       0
#XS Ineff= 2 , 0
       0                               0
Bank Sta=9886.43,10219.26
Exp/Cntr=0.3,0.1

Type RM Length L Ch R = 1 ,37173.42,274.696400,274.696400,274.696400
XS GIS Cut Line= 2
408138.842321545743476.790649489408364.536765993 743254.56842725
#Sta/Elev= 30
9844.434123.28589867.109121.05419875.492120.46349889.745 119.8189903.998118.3144
9923.244114.71969932.505112.25849937.278109.69179951.312101.22969961.01197.04835
9975.26495.43868 9979.3893.550789989.51786.985459993.41385.7006110003.7784.39026
10007.4585.0046710018.0287.2797210021.48 88.372710032.28 92.731710035.5193.21342
10046.5395.3803610063.5897.7901110077.62100.322910091.65103.226110103.54104.5986
10105.68105.034210119.72108.553910133.75111.875410147.78 116.47910161.17120.4455
#Mann= 3 , 0 , 0
9844.434    0.06       09844.434    0.06       010161.17    0.06       0
#XS Ineff= 2 , 0
       0                               0
Bank Sta=9844.434,10161.17
Exp/Cntr=0.3,0.1

Type RM Length L Ch R = 1 ,36898.73,464.332600,464.332600,464.332600
XS GIS Cut Line= 6
408123.344700336743630.777101904408268.643732578743556.853958935
408339.004902571743531.619319528408377.231020123743528.494358674
 408538.88894996 743541.79552792408915.923160493743496.921310082
#Sta/Elev= 30
9682.177124.50989773.632110.18229807.374107.43149862.988106.16939895.087103.5704
9905.504101.62899936.25190.544729966.37188.601839996.68783.3830210006.8283.24624
10016.9385.5407810037.16 95.449610087.3195.4234910107.3192.7781610117.3292.39181
10137.3995.2545510147.4395.7384510207.7195.6951110227.8794.5333910248.0388.77341
10258.11 89.123910288.3594.1226610328.66 93.9327 10358.995.6514410368.9896.68774
10389.14100.853410399.22101.263910429.45 105.58710449.61107.175210500.94113.3766
#Mann= 3 , 0 , 0
9682.177    0.04       09682.177    0.04       010500.94    0.04       0
#XS Ineff= 2 , 0
       0                 10096.7       0
Bank Sta=9682.177,10500.94
Exp/Cntr=0.3,0.1

Type RM Length L Ch R = 1 , 36434.4,464.332600,464.332600,464.332600
XS GIS Cut Line= 6
408124.120748073743883.910249472408248.817626357 743922.86204797
408297.612154365743943.623307928408436.657839626744019.177996099
408491.501655757744044.265965402408613.287407637744089.169625267
#Sta/Elev= 30
9728.398154.2843 9729.31153.71439732.489 150.3729739.685142.2701 9750.06124.0038
9760.435 115.803 9770.81 113.7239823.285113.35249833.878111.95479855.066104.6103
9898.43196.040079909.29994.376629920.40293.572799931.58893.575569965.47992.36029
9979.37187.343469999.43881.7110210011.6481.1844810019.3981.9213110023.19 82.7307
10034.67 89.995910045.9792.4728610084.43 96.9158 10112.698.0929610145.28102.9231
10166.81105.5522 10188.3109.366310198.88111.720410230.64115.217710260.58117.5224
#Mann= 3 , 0 , 0
9728.398  0.0474       09728.398  0.0474       010260.58  0.0474       0
#XS Ineff= 2 , 0
       0                               0
Bank Sta=9728.398,10260.58
Exp/Cntr=0.3,0.1

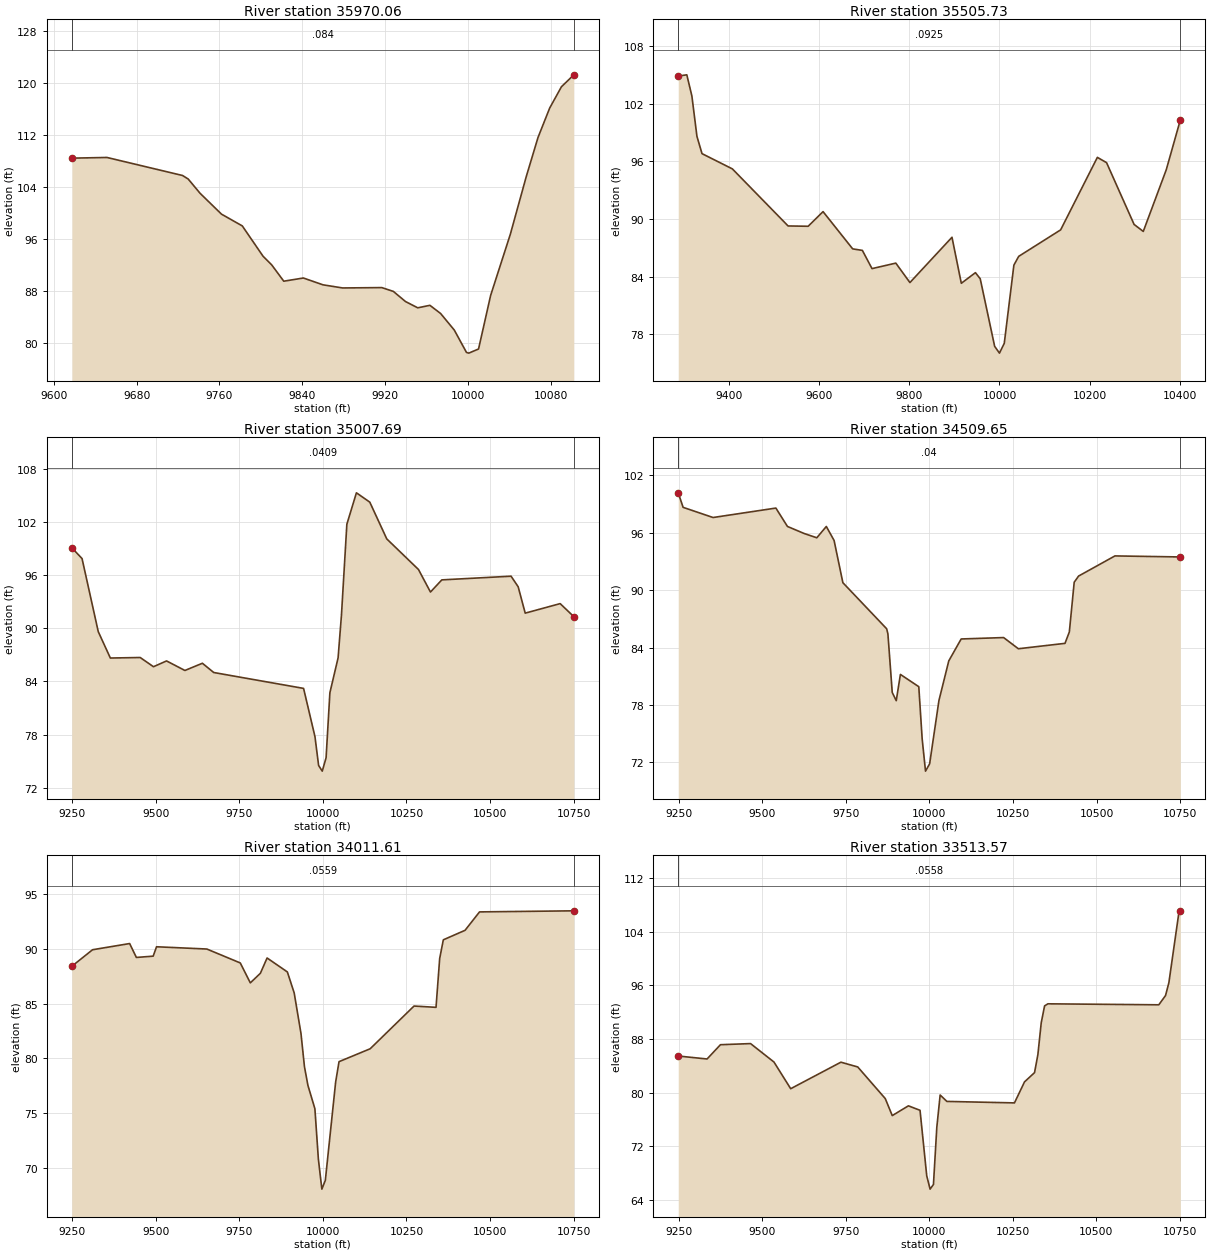
Type RM Length L Ch R = 1 ,35970.06,464.332600,464.332600,464.332600
XS GIS Cut Line= 6
407834.582355499744198.280153319407930.249402553744246.291655511
408013.348904341744293.931266069408165.213328332744388.323322907
408201.306918025744410.045378089408255.592633039744438.680596754
#Sta/Elev= 30
9617.366108.42159651.399108.52679724.404105.7557 9729.88105.21219741.407103.0125
 9762.0299.817089782.12798.007269802.23393.338169810.56792.012399822.21689.50762
9841.159 89.99869860.10288.950819879.045 88.46949916.93288.524369928.10387.93951
9939.87886.376719951.65285.416939963.42685.800089973.76184.543959986.97582.00037
9998.74978.56224   1000178.4518410010.4379.08843 10022.187.3234510041.1396.72036
10056.61105.640610067.91111.615110079.22116.141610090.53 119.399 10102.5121.2298
#Mann= 3 , 0 , 0
9617.366   0.084       09617.366   0.084       0 10102.5   0.084       0
#XS Ineff= 2 , 0
       0                               0
Bank Sta=9617.366,10102.5
Exp/Cntr=0.3,0.1

Type RM Length L Ch R = 1 ,35505.73,498.040800,498.040800,498.040800
XS GIS Cut Line= 6
407368.046350449744498.097472191407605.454592407744619.655159608
 407792.26935938744698.074544549407968.571061164744747.203183532
 408076.55377996 744787.35943912408415.661970228744857.076048449
#Sta/Elev= 30
9287.178104.87979306.224105.00629317.459102.80499328.69498.602219339.92896.80567
9407.33695.217369530.91789.281139575.44489.248559608.51790.771479674.19586.89772
9695.75186.735279717.14284.842039769.95385.414139801.26783.390779894.57688.10527
9915.28883.314949946.55884.419529957.22983.791139989.241 76.75659999.93176.04842
10010.6177.0703610031.9385.2063510042.5986.1162310135.6788.8739410217.1696.41647
10237.54 95.869510298.6589.4391910319.0388.7122210369.9695.1182810401.19100.3004
#Mann= 3 , 0 , 0
9287.178  0.0925       09287.178  0.0925       010401.19  0.0925       0
#XS Ineff= 2 , 0
       09812.693        10176.17       0
Bank Sta=9287.178,10401.19
Exp/Cntr=0.3,0.1

Type RM Length L Ch R = 1 ,35007.69,498.040800,498.040800,498.040800
XS GIS Cut Line= 6
407409.599603012744708.828186156407696.201693839744938.210304741
407963.711693197745283.248569899 408048.78866321745361.351706121
408288.712498742 745499.31830333408574.293886012745596.749458586
#Sta/Elev= 30
9249.13799.099719279.89697.869529328.33489.628899364.52686.646239453.84786.70365
9493.54185.665249532.56886.31913 9587.5985.24171 9639.8286.05597 9673.7285.01212
 9942.4883.218579976.55777.77161 9987.4574.519929998.34273.8811710009.8375.39565
10021.1782.7291510045.6986.66139 10055.891.5002210071.93101.747810100.52105.2919
10140.54104.2389 10191.3100.091410286.1596.6377510322.0194.0947910355.9795.46623
10563.0695.8825210584.3194.6921910605.3991.7117310709.9292.7875710750.8491.31537
#Mann= 3 , 0 , 0
9249.137  0.0409       09249.137  0.0409       010750.84  0.0409       0
#XS Ineff= 2 , 0
       09734.785        10085.43       0
Bank Sta=9249.137,10750.84
Exp/Cntr=0.3,0.1

Type RM Length L Ch R = 1 ,34509.65,498.040800,498.040800,498.040800
XS GIS Cut Line= 6
406941.931772244744872.236618282407223.016268329745032.851026227
407489.921910773745253.212182189407618.526978118745282.552858291
 407770.98711076745572.825103281 408082.95276914745754.627808826
#Sta/Elev= 30
9249.192100.17269263.75998.654569353.37897.591329541.20798.57877 9575.7996.65813
9625.95395.918119663.57595.473229692.02696.655279715.28495.192119741.53790.77904
  9872.5 85.96069876.22685.421799889.17579.299579901.13778.444439913.59381.18935
 9968.55 79.90799978.61974.465889988.66771.08102   1000171.8466710028.8178.46425
10058.2382.60389 10095.384.8953110222.2385.0421910266.3283.8739610405.77 84.4369
10418.75  85.629 10433.390.8271710446.4491.4730110555.16 93.5777 10750.693.46895
#Mann= 3 , 0 , 0
9249.192    0.04       09249.192    0.04       0 10750.6    0.04       0
#XS Ineff= 2 , 0
       09859.833                       0
Bank Sta=9249.192,10750.6
Exp/Cntr=0.3,0.1

Type RM Length L Ch R = 1 ,34011.61,498.040900,498.040900,498.040900
XS GIS Cut Line= 6
 406663.37524084745568.910633234407151.748523309745612.835085374
407287.048846702745602.690659263407486.294229134745562.927303227
407855.394824185745716.358763097408111.330270846745804.634634736
#Sta/Elev= 30
9249.08888.411439311.25589.926859422.211 90.49299442.32489.223789492.60689.34254
9502.66390.198839653.10989.99199 9753.1388.721659783.15486.903479813.21587.77581
9833.33289.174749893.93687.900329914.33485.990339934.73282.278619945.06679.25325
9955.48377.541429976.31975.413869986.73770.808259997.15568.0749810007.5368.87537
10038.4377.8618910048.4979.7100910141.6380.8867910272.8584.7877510338.6284.66971
10349.5889.1297710360.4590.8321910425.4691.70113 10468.8 93.381810750.8693.47966
#Mann= 3 , 0 , 0
9249.088  0.0559       09249.088  0.0559       010750.86  0.0559       0
#XS Ineff= 2 , 0
       0                               0
Bank Sta=9249.088,10750.86
Exp/Cntr=0.3,0.1

Type RM Length L Ch R = 1 ,33513.57,498.040800,498.040800,498.040800
XS GIS Cut Line= 6
406818.816582341746056.281974167407288.882876793746063.016567443
407528.175810861746008.716140237407606.823174464746009.756014645
 407865.52665733  745977.3172727408308.860486216746017.543521626
#Sta/Elev= 30
9249.09485.473529335.35685.030039375.39287.159979465.44787.325359535.47184.57553
9585.47680.599279735.66584.553049786.08983.840549868.30279.132179889.31276.59258
9937.59178.047029972.37477.37929 9992.4367.6086410002.4765.6298410012.5166.32787
10022.5374.8319510032.5479.6601110052.6678.7056210254.8378.4849610284.8581.61467
10314.8883.0007410324.8885.6873210334.8890.4213410344.8892.9436410354.8993.25596
10686.58 93.107810706.7294.4892610716.7996.4247710747.01106.9913 10750.9107.1184
#Mann= 3 , 0 , 0
9249.094  0.0558       09249.094  0.0558       0 10750.9  0.0558       0
#XS Ineff= 2 , 0
       0                               0
Bank Sta=9249.094,10750.9
Exp/Cntr=0.3,0.1