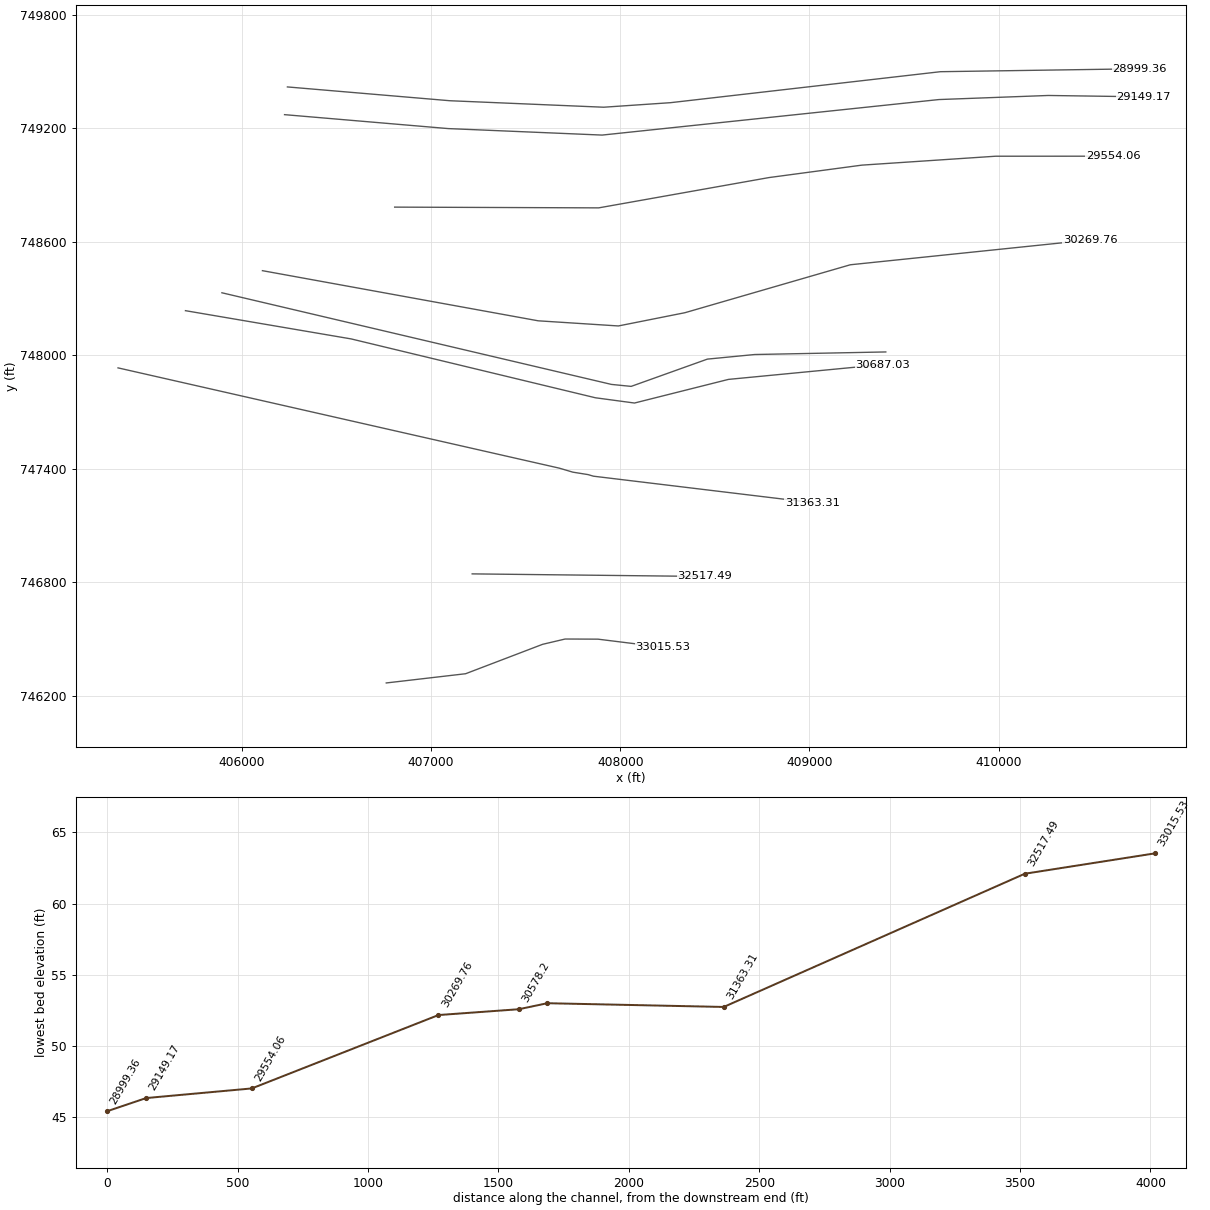
HEC-RAS study 2834_ras.prj: 2834

--- 2834_ras.g01 (geometry) --- (continued)

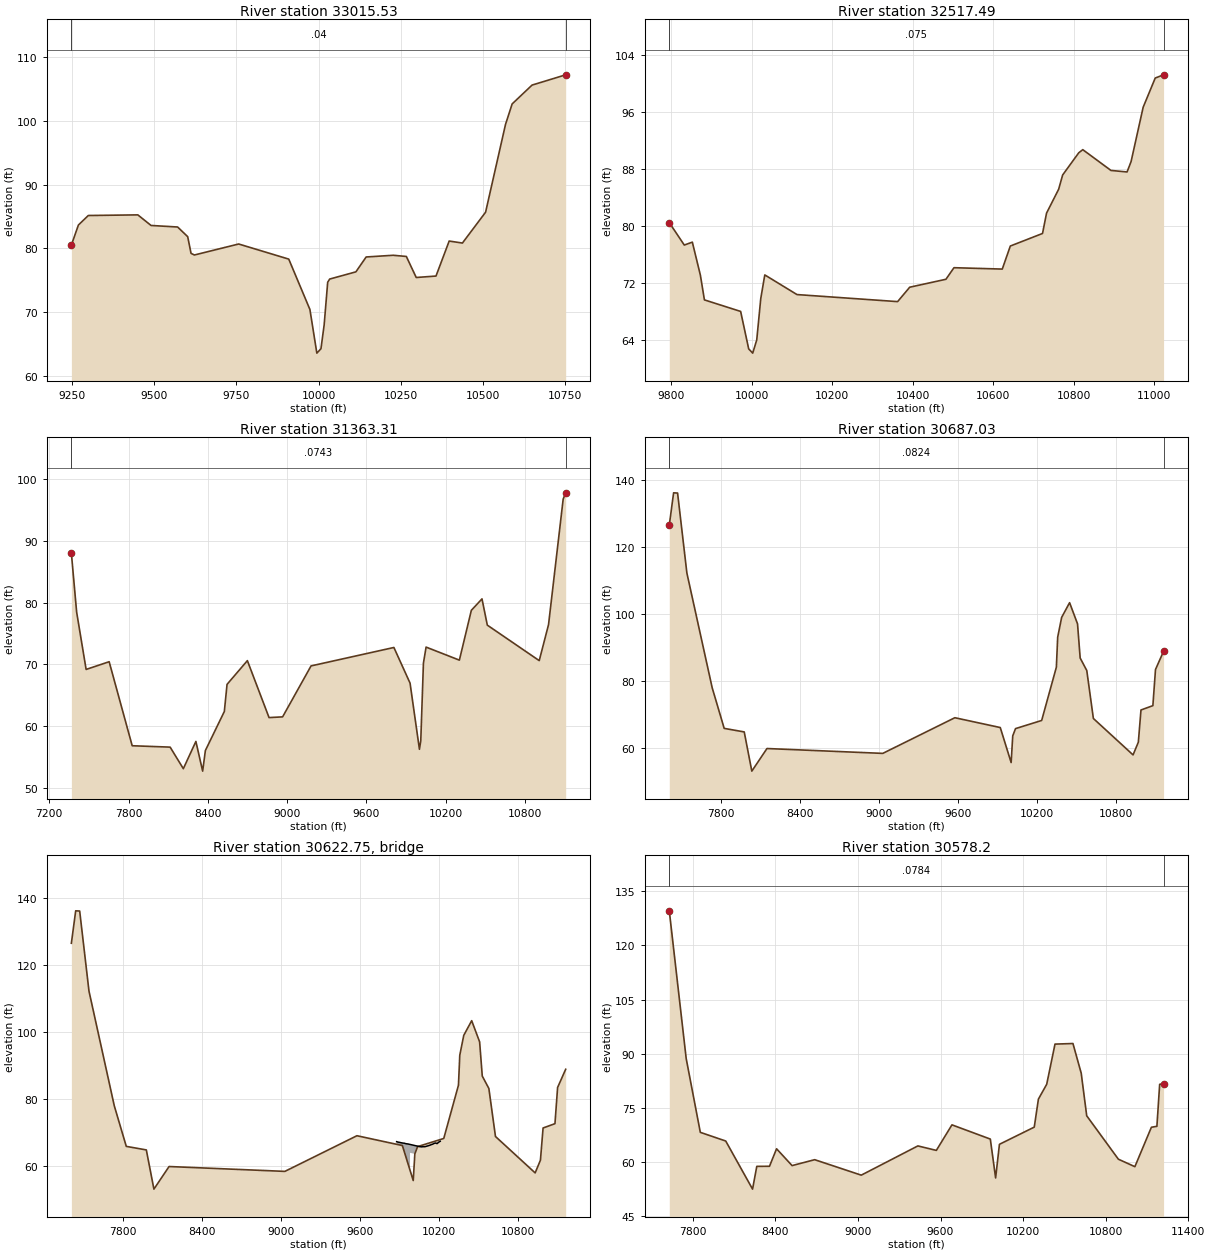
Type RM Length L Ch R = 1 ,33015.53,498.040800,498.040800,498.040800
XS GIS Cut Line= 6
406763.672432174746267.696575539407182.857001324746316.445971867
407589.899791204746471.879881027407708.946020029746499.902660853
407882.193508476746499.177753603 408226.23762297 746456.46589321
#Sta/Elev= 30
9249.12680.506489270.49483.663129300.55185.157599451.012 85.25749491.21583.59229
9571.94183.349779602.49881.831739612.69379.206569622.88978.950189757.41180.67877
 9909.5678.302629973.82970.387079994.88863.5255210007.34 64.2106 10017.167.96475
10027.8274.6652710033.8575.1674410113.4876.2999210144.7578.6393510226.6778.90736
10266.7878.7204310296.8275.4153410356.8975.6412710396.94 81.143710437.1480.82755
10507.5585.6763110568.03 99.467410588.21102.695710648.73105.658310750.85107.2716
#Mann= 3 , 0 , 0
9249.126    0.04       09249.126    0.04       010750.85    0.04       0
#XS Ineff= 2 , 0
       0                10092.92       0
Bank Sta=9249.126,10750.85
Exp/Cntr=0.3,0.1

Type RM Length L Ch R = 1 ,32517.49,1154.170500,1154.170500,1154.170500
XS GIS Cut Line= 2
407217.722856998746844.134810001408445.734053344746830.446787089
#Sta/Elev= 30
9795.53580.413199832.81477.265119852.81577.674389872.81773.030659882.81769.56912
9972.82367.947979992.82462.6929410002.8262.0948710012.83  63.94510022.8369.75951
10032.8373.0724910112.83 70.314910362.85 69.325410392.8571.3467810482.8572.46142
10502.8674.0863810622.8673.8930210642.8677.1287610722.8778.8933210732.8781.75105
10762.8785.0929610772.87 87.103410812.8790.2176210822.8890.6567310892.8887.74119
10932.8887.5253810942.8888.9845810972.8896.6081311002.89100.710311023.62 101.162
#Mann= 3 , 0 , 0
9795.535   0.075       09795.535   0.075       011023.62   0.075       0
#XS Ineff= 2 , 0
       0                10249.25       0
Bank Sta=9795.535,11023.62
Exp/Cntr=0.3,0.1

Type RM Length L Ch R = 1 ,31363.31,676.289400,676.289400,676.289400
XS GIS Cut Line= 6
405346.184942156747932.746183455407678.134001791747402.835057467
407749.574730307747381.686626375407829.997138709747368.754297569
407858.714095384747360.342838332409013.719664395747220.940627918
#Sta/Elev= 30
7366.999 87.98367406.804 78.45447478.58869.177887652.92270.426167827.25656.82887
8114.39556.606088214.26653.118528309.23857.527128360.51352.722588381.02356.05165
8524.59262.373438545.10266.761288698.92670.601668863.00561.386998965.55461.50116
9180.90869.747219807.80972.72969 9930.1266.96121 10001.156.2570910011.1857.62953
10031.3270.2045610051.4772.7929510303.28  70.68110393.9378.7421910474.5280.59568
10514.8176.3465710907.6470.6040610978.1476.4302311088.9496.74299 11107.897.75588
#Mann= 3 , 0 , 0
7366.999  0.0743       07366.999  0.0743       0 11107.8  0.0743       0
#XS Ineff= 2 , 0
       09763.831        10241.29       0
Bank Sta=7366.999,11107.8
Exp/Cntr=0.3,0.1

Type RM Length L Ch R = 1 ,30687.03,108.825500,108.825500,108.825500
XS GIS Cut Line= 6
405702.524121791748235.021122098406578.017523676748085.817722917
407868.884595007747774.760072365408075.481817216747746.982294574
408571.937256962747871.873787642409386.171298424747950.228711293
#Sta/Elev= 30
7407.136126.38267439.937136.05677470.237135.99147540.938112.10247733.312 77.8576
7824.46465.747557976.793 64.68678034.541 52.98628149.683 59.73279030.04158.28204
9577.79368.926229923.06765.9946610005.7155.54534 10017.963.5157210038.9865.67527
10237.7368.1087710349.4584.0077110359.5192.9701910389.6898.8792810450.03103.2673
10510.3496.9409510530.4286.7428610580.6283.0178910630.8168.6992710932.4357.82836
10972.5861.6272710992.6671.23498   1108372.5278411103.0783.3219311164.4188.75326
#Mann= 3 , 0 , 0
7407.136  0.0824       07407.136  0.0824       011164.41  0.0824       0
#XS Ineff= 2 , 0
       09593.206        10440.03       0
Bank Sta=7407.136,11164.41
Exp/Cntr=0.3,0.1

Type RM Length L Ch R = 3 ,30622.75,,,
BEGIN DESCRIPTION:
END DESCRIPTION:
Bridge Culvert--1,0,-1,-1, 0
Deck Dist Width WeirC Skew NumUp NumDn MinLoCord MaxHiCord MaxSubmerge Is_Ogee
31.610950,45.603600,2.6,0, 40, 40, , , 0.95, 0, 0,0,,
 9879.44 9882.82 9893.66 9902.94 9904.50 9915.34 9926.18 9928.86 9937.02 9947.86
 9954.78 9958.70 9964.40 9981.30 9981.3010018.7010018.7010046.7210056.2510058.46
10067.0910077.9310084.3810088.7710099.6110110.3010110.4510121.2910132.1310136.22
10142.9610153.8010162.1410164.6410175.4810186.3210188.0610197.1610208.0010210.63
   67.15   67.11   67.00   66.94   66.92   66.82   66.74   66.73   66.70   66.57
   66.52   66.50   66.48   66.33   66.33   65.99   65.99   65.75   65.66   65.66
   65.60   65.64   65.67   65.64   65.69   65.83   65.83   65.95   66.08   66.17
   66.27   66.40   66.60   66.63   66.75   66.57   66.60   66.94   67.21   67.26
 -932.85 -932.89 -933.00 -933.06 -933.08 -933.18 -933.26 -933.27 -933.30 -933.43
 -933.48 -933.50 -933.52 -933.67   63.83   63.49 -934.01 -934.25 -934.34 -934.34
 -934.40 -934.36 -934.33 -934.36 -934.31 -934.17 -934.17 -934.05 -933.92 -933.83
 -933.73 -933.60 -933.40 -933.37 -933.25 -933.43 -933.40 -933.06 -932.79 -932.74
 9879.44 9882.82 9893.66 9902.94 9904.50 9915.34 9926.18 9928.86 9937.02 9947.86
 9954.78 9958.70 9964.40 9981.30 9981.3010018.7010018.7010046.7210056.2510058.46
10067.0910077.9310084.3810088.7710099.6110110.3010110.4510121.2910132.1310136.22
10142.9610153.8010162.1410164.6410175.4810186.3210188.0610197.1610208.0010210.63
   67.15   67.11   67.00   66.94   66.92   66.82   66.74   66.73   66.70   66.57
   66.52   66.50   66.48   66.33   66.33   65.99   65.99   65.75   65.66   65.66
   65.60   65.64   65.67   65.64   65.69   65.83   65.83   65.95   66.08   66.17
   66.27   66.40   66.60   66.63   66.75   66.57   66.60   66.94   67.21   67.26
 -932.85 -932.89 -933.00 -933.06 -933.08 -933.18 -933.26 -933.27 -933.30 -933.43
 -933.48 -933.50 -933.52 -933.67   63.83   63.49 -934.01 -934.25 -934.34 -934.34
 -934.40 -934.36 -934.33 -934.36 -934.31 -934.17 -934.17 -934.05 -933.92 -933.83
 -933.73 -933.60 -933.40 -933.37 -933.25 -933.43 -933.40 -933.06 -932.79 -932.74
BR Coef=-1 , 0 , 0 ,, 0 ,,,0.8,0,1,0,
WSPro=,,,, 1 ,,,, 0 ,,,, 0 ,,,,-1 ,-1 ,-1 , 0 , 0 , 0 , 0 , 0
BC Design=,, 0 ,, 0 ,,,,,,

Type RM Length L Ch R = 1 , 30578.2,308.443700,308.443700,308.443700
XS GIS Cut Line= 6
405895.198128998748329.600178331407953.664687663747845.361924216
408057.831354231 747834.94525753408460.609131962747979.042479768
408710.609131962748003.348035306409403.476608843748016.947572365
#Sta/Elev= 30
7628.747129.54547751.66888.666077854.27168.270158038.957 65.86978233.90352.56399
8264.68458.858188357.02858.885328408.32963.726018521.19359.071398685.358 60.7071
9023.94956.42935 9435.3164.516449569.45863.273889682.96970.343429961.79566.40747
10000.3155.6632910028.05 64.961510281.1269.71425 10311.377.4659610371.5981.56886
10431.85 92.679910562.2892.8388410622.2984.64025 10662.3 72.848610892.3460.84235
11012.3758.7741111132.39 69.6803 11172.469.93562 11192.481.5430411220.8881.77355
#Mann= 3 , 0 , 0
7628.747  0.0784       07628.747  0.0784       011220.88  0.0784       0
#XS Ineff= 2 , 0
       09660.725        10453.61       0
Bank Sta=7628.747,11220.88
Exp/Cntr=0.3,0.1

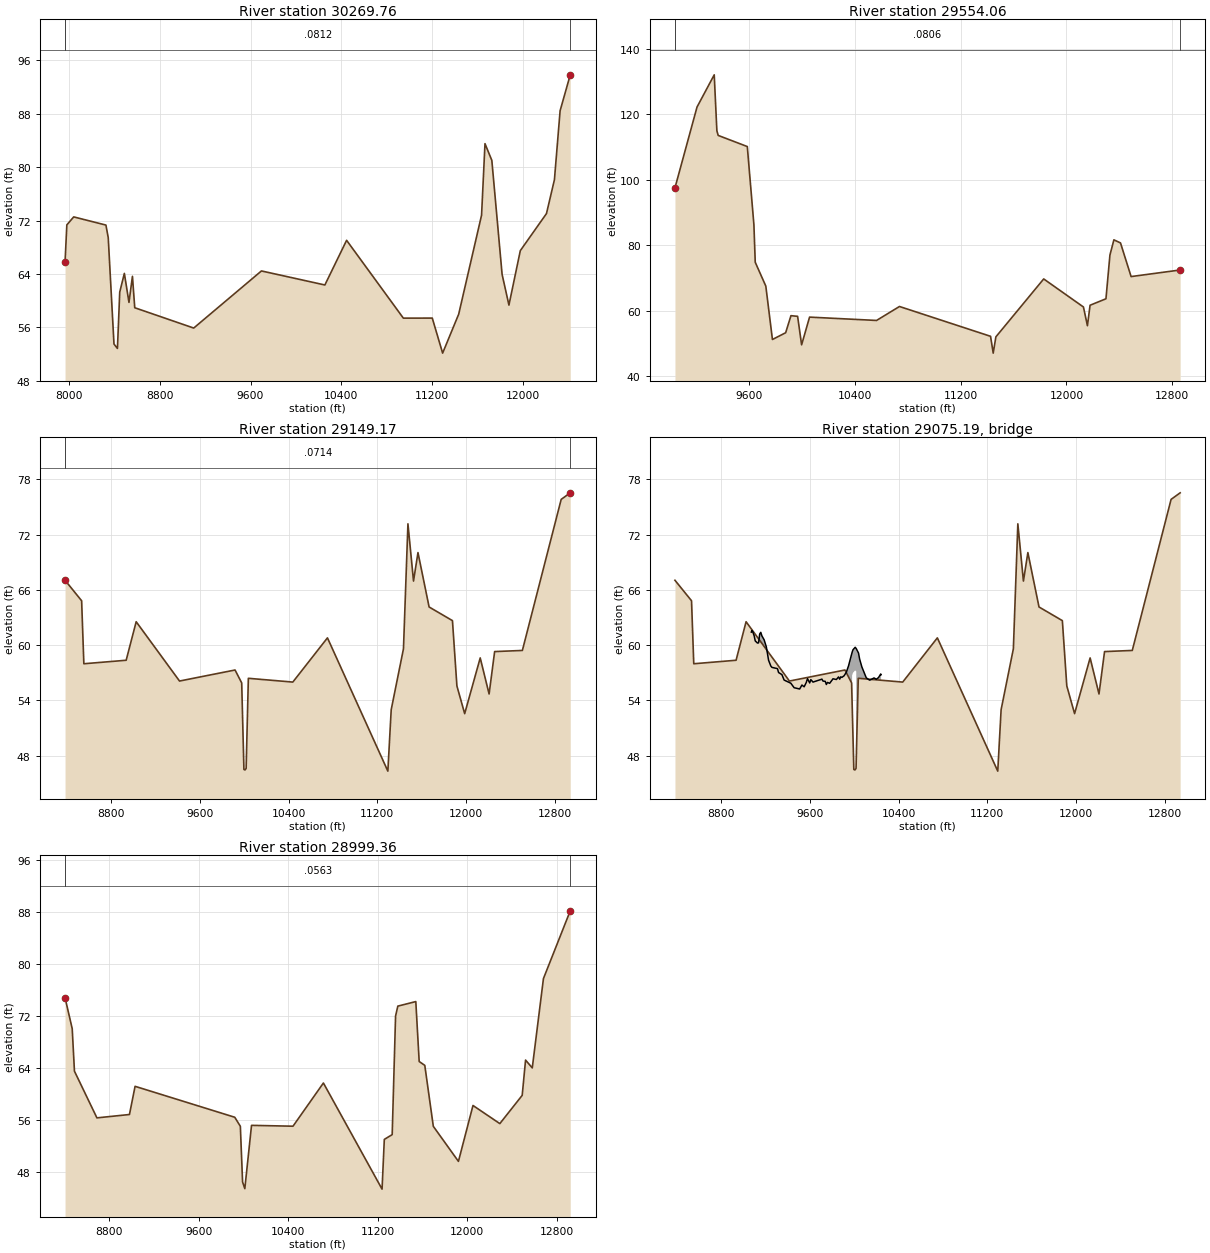
Type RM Length L Ch R = 1 ,30269.76,715.700600,715.700600,715.700600
XS GIS Cut Line= 6
406109.375486506  748446.4325552407566.472800149748181.503289433
 407990.27219878748154.291861923 408342.23124714748224.360107111
409215.910072757748477.598996149410484.288200137748609.046900395
#Sta/Elev= 30
7964.96565.760837980.763 71.35738041.42972.551888325.36271.327188345.64869.44081
8396.36453.510978426.79452.857848447.09761.295048487.79364.093658528.48859.74542
8559.00963.658198579.35758.950579099.11655.907679696.15364.46007 10255.362.35763
10446.89  69.04510947.0257.3935111202.04 57.399411293.3452.1534411434.9357.98815
11636.5172.8086611666.7383.5198111727.0681.0143411817.5263.9482211877.7659.34624
11978.13 67.499612208.6873.0499512278.8178.1213612328.8888.4540412418.2693.82732
#Mann= 3 , 0 , 0
7964.965  0.0812       07964.965  0.0812       012418.26  0.0812       0
#XS Ineff= 2 , 0
       0 9599.02        10463.27       0
Bank Sta=7964.965,12418.26
Exp/Cntr=0.3,0.1

Type RM Length L Ch R = 1 ,29554.06,404.888300,404.888300,404.888300
XS GIS Cut Line= 6
406808.091770887748782.247051522407886.315495491748778.322322771
408786.290308386748938.444451675409277.031417936749004.136826187
409983.366333067749051.209795401410605.836334497749051.409722775
#Sta/Elev= 30
9040.45897.513229207.368122.23399337.369132.08029357.369114.96879367.369113.5532
9587.371110.14979637.37186.219799647.37274.774399727.37267.484619777.373 51.1591
9877.37453.226389917.37458.44074 9967.7358.241559997.95349.5260410058.0258.00035
10564.5656.9817710737.7661.2505111426.2752.1322211446.3946.9907811466.52 51.9654
11828.0869.6736112128.56 61.090412158.5855.36798 12178.661.6286912298.6563.60886
12328.6676.9622112358.6781.6295212408.6880.6846812488.6870.3981612859.5672.40934
#Mann= 3 , 0 , 0
9040.458  0.0806       09040.458  0.0806       012859.56  0.0806       0
#XS Ineff= 2 , 0
       09683.778        10797.93       0
Bank Sta=9040.458,12859.56
Exp/Cntr=0.3,0.1

Type RM Length L Ch R = 1 ,29149.17,149.810600,149.810600,149.810600
XS GIS Cut Line= 6
406226.187185794749270.914595619407091.125854641749197.277319252
407904.283019453749162.962140858409683.779626846749350.662932873
410262.174633235749372.291710898410766.658211827749365.043465629
#Sta/Elev= 30
8383.68867.035778533.20164.809198553.29457.97105 8934.8258.350469025.12462.53359
9415.99256.094239916.67957.292349976.68255.889859996.68346.4960710006.6946.44234
10016.6946.6048710036.6956.3917510437.6455.9813910749.9760.7820111294.6946.31373
11324.8752.9833811435.5159.6004511475.7473.1643511526.0466.9492911566.2470.03978
11666.6464.1351411877.2362.6526611917.2955.5643711987.4152.5545712127.56 58.6045
12207.6254.6902912257.6359.2936612507.6759.4148912857.7275.8176612939.4276.52867
#Mann= 3 , 0 , 0
8383.688  0.0714       08383.688  0.0714       012939.42  0.0714       0
#XS Ineff= 2 , 0
       09615.233        10722.12       0
Bank Sta=8383.688,12939.42
Exp/Cntr=0.3,0.1

Type RM Length L Ch R = 3 ,29075.19,,,
BEGIN DESCRIPTION:
END DESCRIPTION:
Bridge Culvert--1,0,-1,-1, 0
Deck Dist Width WeirC Skew NumUp NumDn MinLoCord MaxHiCord MaxSubmerge Is_Ogee
53.415850,42.978900,2.6,0, 60, 60, , , 0.95, 0, 0,0,,
 9072.29 9077.57 9087.60 9097.62 9107.64 9127.69 9137.72 9147.74 9157.77 9167.79
 9187.84 9207.89 9227.94 9247.99 9258.01 9308.11 9318.13 9348.19 9368.23 9428.34
 9458.40 9508.10 9528.53 9548.57 9568.61 9578.63 9598.66 9608.68 9628.72 9708.87
 9718.89 9738.91 9748.92 9758.93 9778.95 9808.98 9839.01 9859.03 9869.04 9879.04
 9889.04 9909.04 9929.04 9949.05 9981.14 9981.14 9989.0510009.0510018.8610018.86
10039.0510049.0510069.0610109.1010139.1510179.2210199.2510219.2910239.3210242.33
   61.41   61.58   61.37   61.02   60.45   60.22   60.24   61.20   61.38   61.00
   60.57   59.80   58.35   57.73   57.58   57.44   57.02   56.79   56.20   55.86
   55.37   55.23   55.66   55.47   55.96   56.36   55.89   56.25   55.98   56.30
   56.09   56.06   55.72   55.94   55.85   56.34   56.26   56.54   56.30   56.55
   56.49   56.67   57.05   57.75   59.21   59.21   59.49   59.76   59.61   59.61
   59.13   58.48   57.63   56.44   56.19   56.43   56.29   56.47   56.86   56.78
 -938.59 -938.42 -938.63 -938.98 -939.55 -939.78 -939.76 -938.80 -938.62 -939.00
 -939.43 -940.20 -941.65 -942.27 -942.42 -942.56 -942.98 -943.21 -943.80 -944.14
 -944.63 -944.77 -944.34 -944.53 -944.04 -943.64 -944.11 -943.75 -944.02 -943.70
 -943.91 -943.94 -944.28 -944.06 -944.15 -943.66 -943.74 -943.46 -943.70 -943.45
 -943.51 -943.33 -942.95 -942.25 -940.79   56.71   56.99   57.26   57.11 -940.39
 -940.87 -941.52 -942.37 -943.56 -943.81 -943.57 -943.71 -943.53 -943.14 -943.22
 9072.29 9077.57 9087.60 9097.62 9107.64 9127.69 9137.72 9147.74 9157.77 9167.79
 9187.84 9207.89 9227.94 9247.99 9258.01 9308.11 9318.13 9348.19 9368.23 9428.34
 9458.40 9508.10 9528.53 9548.57 9568.61 9578.63 9598.66 9608.68 9628.72 9708.87
 9718.89 9738.91 9748.92 9758.93 9778.95 9808.98 9839.01 9859.03 9869.04 9879.04
 9889.04 9909.04 9929.04 9949.05 9981.14 9981.14 9989.0510009.0510018.8610018.86
10039.0510049.0510069.0610109.1010139.1510179.2210199.2510219.2910239.3210242.33
   61.41   61.58   61.37   61.02   60.45   60.22   60.24   61.20   61.38   61.00
   60.57   59.80   58.35   57.73   57.58   57.44   57.02   56.79   56.20   55.86
   55.37   55.23   55.66   55.47   55.96   56.36   55.89   56.25   55.98   56.30
   56.09   56.06   55.72   55.94   55.85   56.34   56.26   56.54   56.30   56.55
   56.49   56.67   57.05   57.75   59.21   59.21   59.49   59.76   59.61   59.61
   59.13   58.48   57.63   56.44   56.19   56.43   56.29   56.47   56.86   56.78
 -938.59 -938.42 -938.63 -938.98 -939.55 -939.78 -939.76 -938.80 -938.62 -939.00
 -939.43 -940.20 -941.65 -942.27 -942.42 -942.56 -942.98 -943.21 -943.80 -944.14
 -944.63 -944.77 -944.34 -944.53 -944.04 -943.64 -944.11 -943.75 -944.02 -943.70
 -943.91 -943.94 -944.28 -944.06 -944.15 -943.66 -943.74 -943.46 -943.70 -943.45
 -943.51 -943.33 -942.95 -942.25 -940.79   56.71   56.99   57.26   57.11 -940.39
 -940.87 -941.52 -942.37 -943.56 -943.81 -943.57 -943.71 -943.53 -943.14 -943.22
BR Coef=-1 , 0 , 0 ,, 0 ,,,0.8,0,1,0,
WSPro=,,,, 1 ,,,, 0 ,,,, 0 ,,,,-1 ,-1 ,-1 , 0 , 0 , 0 , 0 , 0
BC Design=,, 0 ,, 0 ,,,,,,

Type RM Length L Ch R = 1 ,28999.36,271.433800,271.433800,271.433800
XS GIS Cut Line= 6
406241.256290764749417.412463158407099.459188044749344.499541461
407912.616352767749310.184363067408265.875852734749334.192403361
 409692.11296019749497.885155082410744.655590832749513.479373977
#Sta/Elev= 30
8403.91374.790238467.95770.036948488.049 63.50498688.975 56.33228980.04556.84903
9030.21361.178699921.79656.426989971.79955.03992  9991.846.48105 10011.845.45678
10071.8155.1821810442.7155.0524510714.6561.6872411239.2745.3865711259.4353.02533
11329.9453.7590311360.1171.9708711380.2373.4964311541.1674.1966611571.3264.99259
11621.5264.3972111697.7655.03403 11922.449.6500912052.6158.2344812292.7655.45061
12492.7959.7931412522.7965.2109712582.7964.0063412682.7977.7301912922.51 88.1368
#Mann= 3 , 0 , 0
8403.913  0.0563       08403.913  0.0563       012922.51  0.0563       0
#XS Ineff= 2 , 0
       09611.681        10728.68       0
Bank Sta=8403.913,12922.51
Exp/Cntr=0.3,0.1