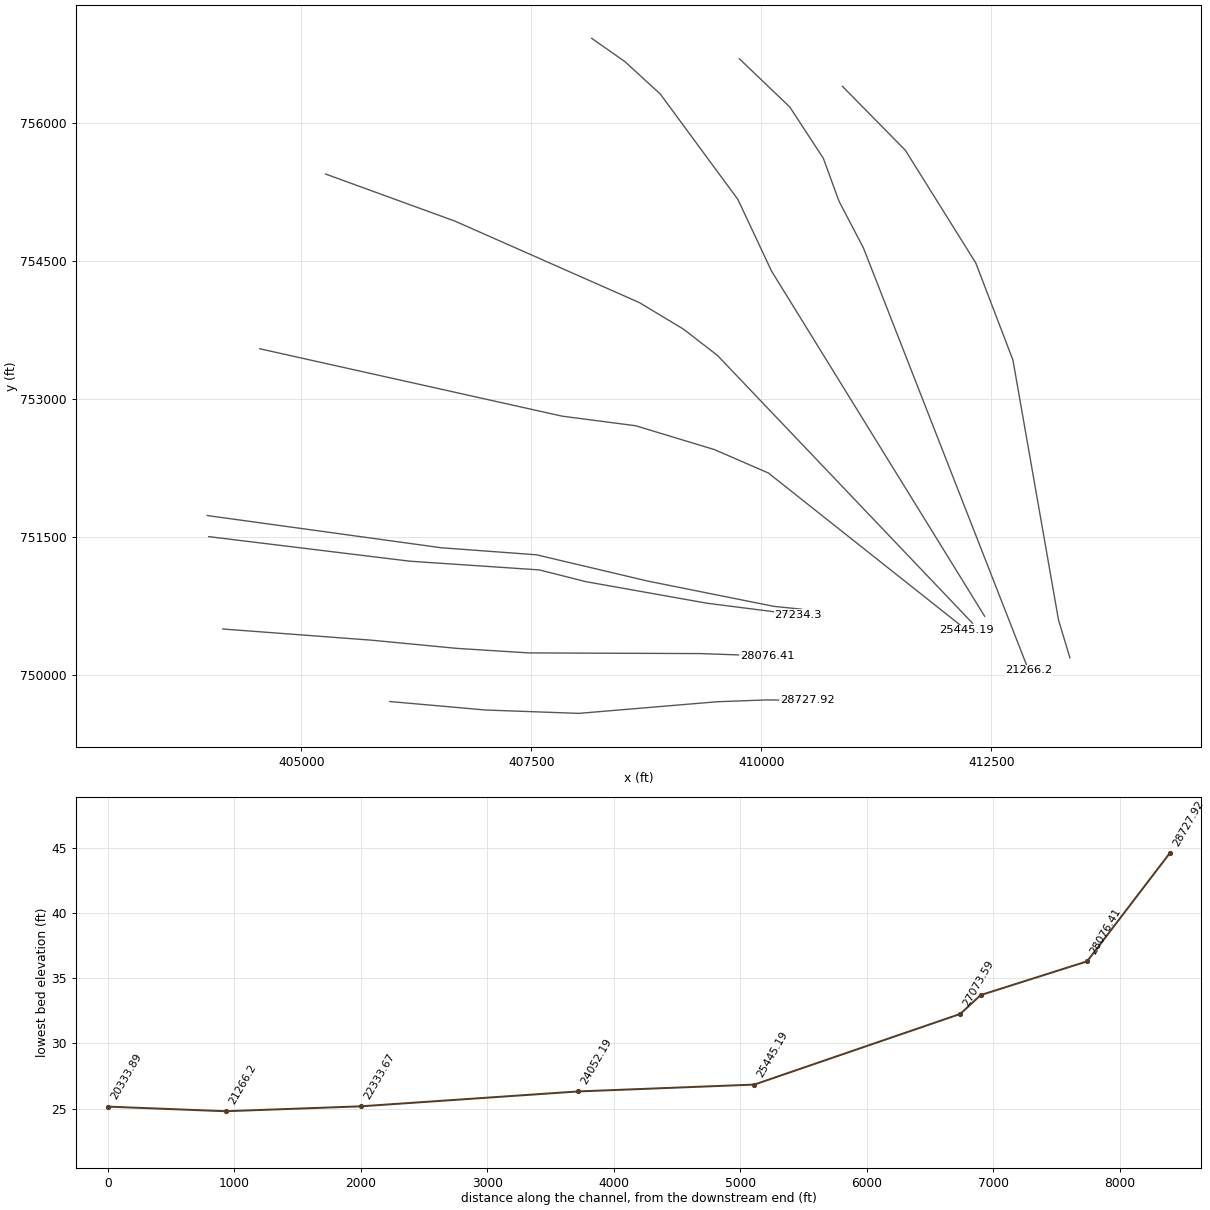
HEC-RAS study 2834_ras.prj: 2834

--- 2834_ras.g01 (geometry) --- (continued)

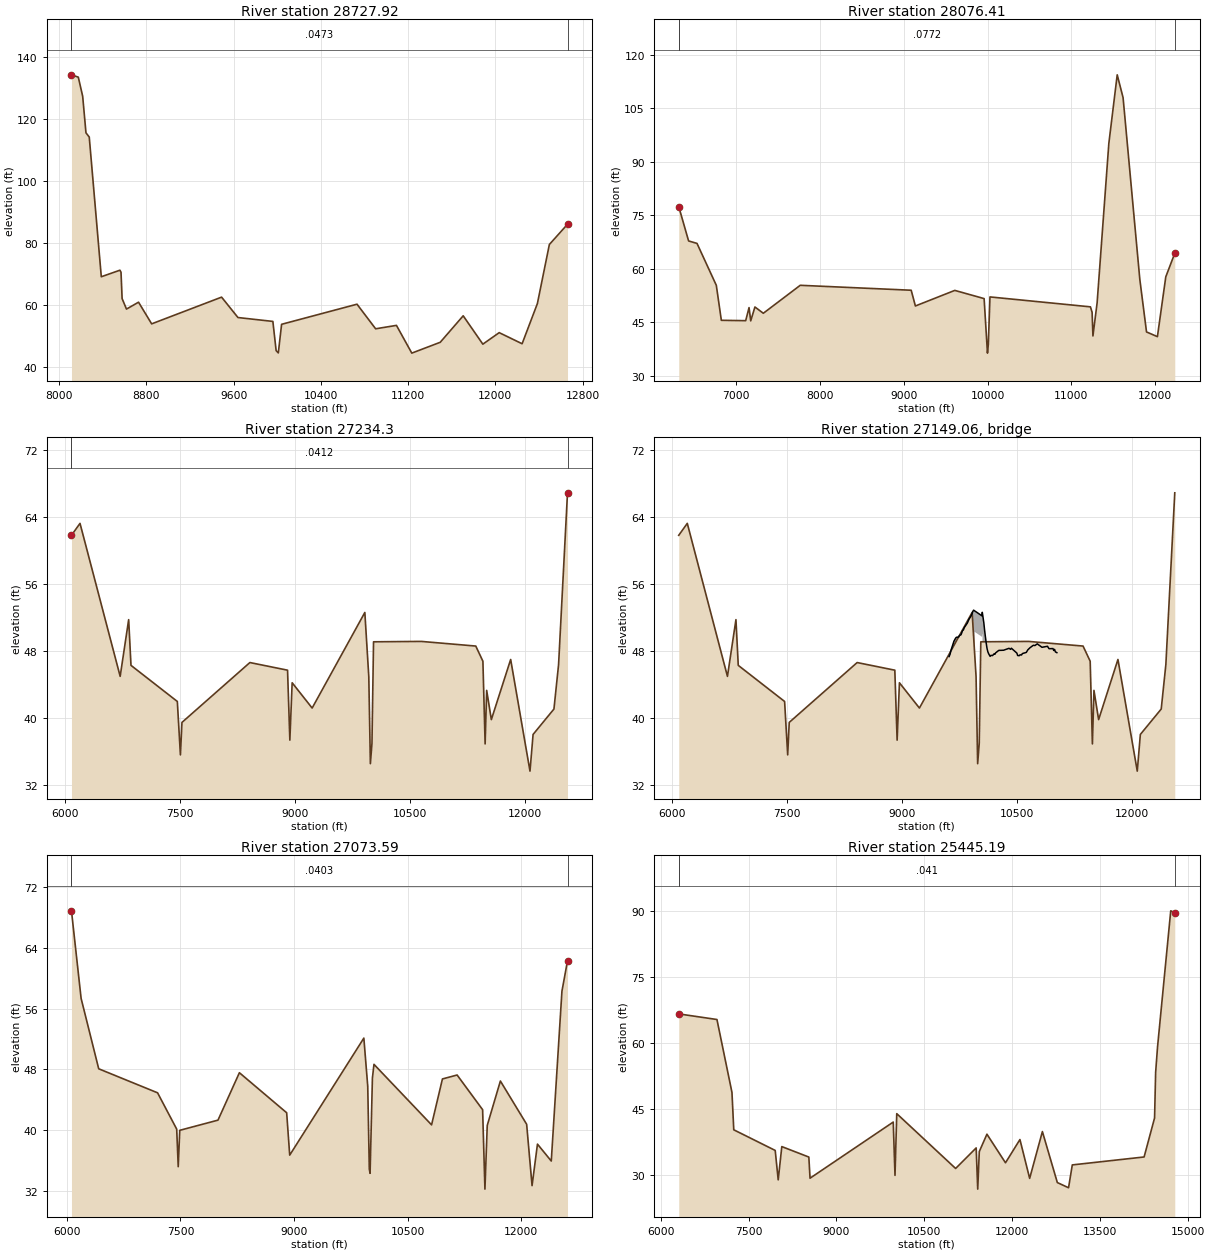
Type RM Length L Ch R = 1 ,28727.92,651.514700,651.514700,651.514700
XS GIS Cut Line= 6
  405962.7272034749707.764633556407004.068816728749615.624813875
408016.545282728749579.039939319409521.396029777749705.470657741
410059.638024992749725.260488962410501.230201433749721.334801387
#Sta/Elev= 30
8112.108134.25188174.729 133.5078214.929127.34698245.067115.56718275.205114.1973
8385.71169.174348556.49271.285458566.53870.635968576.58462.132668616.76858.75261
8727.24860.97602 8847.6653.992679489.01262.604629639.14756.03213 9959.3154.78076
9989.32545.3612310009.3344.6300510039.3353.8497410730.99 60.328610901.8652.40273
11092.83 53.503211233.4844.5606211494.4148.0549711704.9456.5889111885.1847.44916
12035.2851.1605612245.3247.5830712385.3260.5187312495.3379.5728512661.5986.09006
#Mann= 3 , 0 , 0
8112.108  0.0473       08112.108  0.0473       012661.59  0.0473       0
#XS Ineff= 2 , 0
       09583.584        10718.85       0
Bank Sta=8112.108,12661.59
Exp/Cntr=0.3,0.1

Type RM Length L Ch R = 1 ,28076.41,842.103300,842.103300,842.103300
XS GIS Cut Line= 6
404147.478747308750496.227492347405765.459069669750374.562164769
406687.363629788750285.952345163407469.709444642750236.345005974
409342.361308426750228.930148676410062.131898344750203.481495664
#Sta/Elev= 30
6311.34777.38235  6429.267.744086529.48267.060356760.13255.311226820.30145.49459
 7111.1245.390657151.233 49.05227171.28945.33686 7221.4349.230917321.71347.46651
7762.95555.311229088.29653.924529138.42649.511549609.25753.880749959.47551.58191
9999.47636.2913310009.4838.6424910029.4852.04945 11229.549.26821 11249.547.73282
 11259.541.10805 11309.550.40871 11449.595.09796 11549.5114.328111619.51107.9378
11819.5756.9704611899.6242.2311112029.7240.9079912129.8657.6920612237.16 64.2877
#Mann= 3 , 0 , 0
6311.347  0.0772       06311.347  0.0772       012237.16  0.0772       0
#XS Ineff= 2 , 0
       0 9520.24        10795.09       0
Bank Sta=6311.347,12237.16
Exp/Cntr=0.3,0.1

Type RM Length L Ch R = 1 , 27234.3,160.719500,160.719500,160.719500
XS GIS Cut Line= 6
403994.387343824 751500.27367188406182.083015203751233.107553124
407587.638570756751138.663108677408093.194126338751010.885330915
409412.008871555750776.228533015410400.350151345750650.624185503
#Sta/Elev= 30
6089.61161.807456201.046 63.23036724.90944.997336835.72651.756096865.949 46.3078
7470.40742.003917510.70435.637047530.85239.508418416.79346.643278908.053 45.7324
 8938.1337.396288968.20744.232569228.87541.219989916.275  52.6119967.847 44.9575
9988.47634.5876110009.1136.9986310029.7349.1151310652.2849.1616611363.2748.60734
11456.2246.8001611485.1636.9454911505.4743.3256511566.3939.84313 11818.447.00933
12070.4133.7021412110.73 38.0745 12382.941.1036912443.3946.4054212559.67 66.8705
#Mann= 3 , 0 , 0
6089.611  0.0412       06089.611  0.0412       012559.67  0.0412       0
#XS Ineff= 2 , 0
       09582.144        10993.71       0
Bank Sta=6089.611,12559.67
Exp/Cntr=0.3,0.1

Type RM Length L Ch R = 3 ,27149.06,,,
BEGIN DESCRIPTION:
END DESCRIPTION:
Bridge Culvert--1,0,-1,-1, 0
Deck Dist Width WeirC Skew NumUp NumDn MinLoCord MaxHiCord MaxSubmerge Is_Ogee
59.864750,40.990000,2.6,0, 60, 60, , , 0.95, 0, 0,0,,
 9616.27 9628.92 9638.98 9679.30 9699.82 9710.08 9740.86 9751.12 9771.64 9792.16
 9802.42 9812.68 9853.72 9874.25 9905.03 9925.55 9935.81 9948.02 9948.0210046.53
10048.6710051.9810051.9810069.1910079.4510099.9710110.2310120.4910130.7510151.27
10161.5310182.0510202.5710212.8310223.0910264.1310325.6910397.5110418.0210428.26
10499.9210510.1510530.6310540.8610561.3410571.5710622.7610643.2310673.9410714.89
10735.3710766.0810827.5010899.1610919.6310970.8110981.0510991.2911001.5311021.45
   47.36   47.65   48.06   49.19   49.53   49.65   49.69   49.86   49.96   50.47
   50.52   50.79   51.35   51.78   52.24   52.74   52.89   52.81   52.81   52.20
   52.63   52.45   52.45   51.37   50.47   48.96   48.35   47.96   47.71   47.38
   47.50   47.47   47.68   47.63   47.80   48.09   48.11   48.34   48.22   48.35
   47.77   47.48   47.46   47.56   47.55   47.71   47.85   48.16   48.43   48.70
   48.67   48.87   48.46   48.58   48.29   48.31   48.08   48.21   47.92   47.82
 -952.64 -952.35 -951.94 -950.81 -950.47 -950.35 -950.31 -950.14 -950.04 -949.53
 -949.48 -949.21 -948.65 -948.22 -947.76 -947.26 -947.11 -947.19   50.31   49.70
   50.13   49.95 -947.55 -948.63 -949.53 -951.04 -951.65 -952.04 -952.29 -952.62
 -952.50 -952.53 -952.32 -952.37 -952.20 -951.91 -951.89 -951.66 -951.78 -951.65
 -952.23 -952.52 -952.54 -952.44 -952.45 -952.29 -952.15 -951.84 -951.57 -951.30
 -951.33 -951.13 -951.54 -951.42 -951.71 -951.69 -951.92 -951.79 -952.08 -952.18
 9616.27 9628.92 9638.98 9679.30 9699.82 9710.08 9740.86 9751.12 9771.64 9792.16
 9802.42 9812.68 9853.72 9874.25 9905.03 9925.55 9935.81 9948.02 9948.0210046.53
10048.6710051.9810051.9810069.1910079.4510099.9710110.2310120.4910130.7510151.27
10161.5310182.0510202.5710212.8310223.0910264.1310325.6910397.5110418.0210428.26
10499.9210510.1510530.6310540.8610561.3410571.5710622.7610643.2310673.9410714.89
10735.3710766.0810827.5010899.1610919.6310970.8110981.0510991.2911001.5311021.45
   47.36   47.65   48.06   49.19   49.53   49.65   49.69   49.86   49.96   50.47
   50.52   50.79   51.35   51.78   52.24   52.74   52.89   52.81   52.81   52.20
   52.63   52.45   52.45   51.37   50.47   48.96   48.35   47.96   47.71   47.38
   47.50   47.47   47.68   47.63   47.80   48.09   48.11   48.34   48.22   48.35
   47.77   47.48   47.46   47.56   47.55   47.71   47.85   48.16   48.43   48.70
   48.67   48.87   48.46   48.58   48.29   48.31   48.08   48.21   47.92   47.82
 -952.64 -952.35 -951.94 -950.81 -950.47 -950.35 -950.31 -950.14 -950.04 -949.53
 -949.48 -949.21 -948.65 -948.22 -947.76 -947.26 -947.11 -947.19   50.31   49.70
   50.13   49.95 -947.55 -948.63 -949.53 -951.04 -951.65 -952.04 -952.29 -952.62
 -952.50 -952.53 -952.32 -952.37 -952.20 -951.91 -951.89 -951.66 -951.78 -951.65
 -952.23 -952.52 -952.54 -952.44 -952.45 -952.29 -952.15 -951.84 -951.57 -951.30
 -951.33 -951.13 -951.54 -951.42 -951.71 -951.69 -951.92 -951.79 -952.08 -952.18
BR Coef=-1 , 0 , 0 ,, 0 ,,,0.8,0,1,0,
WSPro=,,,, 1 ,,,, 0 ,,,, 0 ,,,,-1 ,-1 ,-1 , 0 , 0 , 0 , 0 , 0
BC Design=,, 0 ,, 0 ,,,,,,

Type RM Length L Ch R = 1 ,27073.59,1628.395400,1628.395400,1628.395400
XS GIS Cut Line= 6
403978.762343794751729.440338567 406522.57780692 751379.24470593
407557.300029099 751302.85581702408768.411140233751016.744705945
410137.269288272750742.374366343410438.113094668750711.773638577
#Sta/Elev= 30
6061.08668.844076188.51457.324076420.683 48.07917197.94544.921477450.30340.14752
7470.49235.21008 7490.6839.992257995.39641.329258278.03747.562928902.05642.30138
8942.16536.730249920.94952.114069972.32545.779399992.87634.9004610003.1534.34192
10033.9846.8680810054.5348.66413 10814.9 40.709910958.3946.7439411152.1747.26235
11488.7442.7047511519.3332.2615111549.9340.6388411723.3146.4728612070.0740.78627
12141.4732.7183912212.8638.1769212395.1535.9559212535.8758.2750812609.3662.26602
#Mann= 3 , 0 , 0
6061.086  0.0403       06061.086  0.0403       012609.36  0.0403       0
#XS Ineff= 2 , 0
       09604.427        11020.14       0
Bank Sta=6061.086,12609.36
Exp/Cntr=0.3,0.1

Type RM Length L Ch R = 1 ,25445.19,1392.997800,1392.997800,1392.997800
XS GIS Cut Line= 6
404548.793479264753542.497302443407837.596927613752809.614628211
 408635.42656818752705.639403403 409491.08510375 752446.43545036
410077.771224767752192.084375292 412235.14838171750482.251902416
#Sta/Elev= 30
6309.30666.633626961.11865.35887 7217.2548.801727247.98640.31658 7954.91  35.634
8006.137 28.94918067.60936.502968528.64634.129078549.137 29.32549968.43642.07244
9998.53529.9697810028.6243.9787311032.88 31.534511383.2436.2046911409.7626.84654
11436.6435.3775211566.77 39.318211883.45 32.826312129.8838.1027512295.7629.28887
12512.9839.9143612767.8828.3383112959.27 27.159713023.0732.3444514248.0234.14742
14426.6642.9995214444.9453.3521914477.1459.1116314702.5490.0367114771.3689.59032
#Mann= 3 , 0 , 0
6309.306   0.041       06309.306   0.041       014771.36   0.041       0
#XS Ineff= 2 , 0
       0 9494.39        11065.38       0
Bank Sta=6309.306,14771.36
Exp/Cntr=0.3,0.1

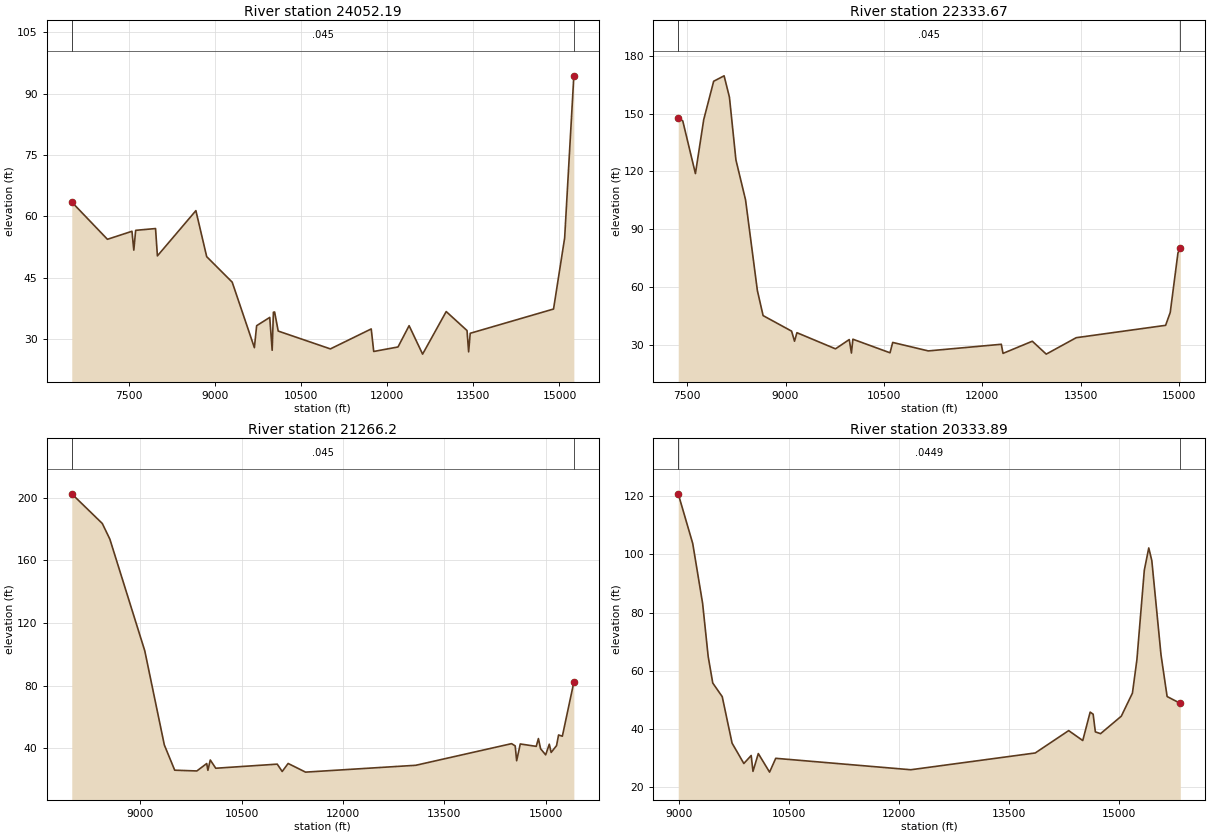
Type RM Length L Ch R = 1 ,24052.19,1718.518500,1718.518500,1718.518500
XS GIS Cut Line= 6
405265.100587696755441.701475069406671.563275993754929.651395321
408675.039503336754044.725765467409155.231975019753755.622950569
409523.183787048753471.217995927412297.087762535750559.147157058
#Sta/Elev= 30
6511.87463.515567132.67454.406467559.44956.36797 7591.5851.760447623.85856.59866
7969.75457.03632 8002.2950.349228671.88161.417628860.12250.162929304.117 43.9169
9690.04427.905479729.33233.277459957.214 35.29759999.635 27.264710020.9836.56639
10041.8336.62576 10104.731.9615911012.81 27.598811723.5432.4834311767.0326.96995
12189.4828.0719212382.8333.2791312617.6126.3207313028.4136.7326613390.8832.08529
13418.6326.8758513446.2531.4189314896.3837.3511215089.7354.7300515249.7394.39027
#Mann= 3 , 0 , 0
6511.874   0.045       06511.874   0.045       015249.73   0.045       0
#XS Ineff= 2 , 0
       09801.371        11826.32       0
Bank Sta=6511.874,15249.73
Exp/Cntr=0.3,0.1

Type RM Length L Ch R = 1 ,22333.67,1067.477200,1067.477200,1067.477200
XS GIS Cut Line= 6
408157.589111209756916.948306233408517.987791866756664.104825765
408902.762479961 756311.58471404409746.740540296755165.483962595
410111.132158905754389.098612264412429.032206953750634.233962595
#Sta/Elev= 30
7363.663147.71577432.605146.16297625.898118.83677752.271146.80787904.096166.7328
8063.057169.54728144.696 158.4298243.678125.89148390.308105.20418570.70158.14632
8658.06145.164049092.557 37.10739137.16831.879949174.00236.29576 9762.0627.92472
9971.94632.7387310005.0925.7434810027.18 32.917910593.6925.8684710634.5231.24138
11177.0326.8460212290.7830.2920212316.9625.5593512763.5331.8715312976.1225.17974
13433.0233.6990114796.6140.1144914867.1246.7932314984.6477.62402 15020.880.40372
#Mann= 3 , 0 , 0
7363.663   0.045       07363.663   0.045       0 15020.8   0.045       0
#XS Ineff= 2 , 0
       09769.312        12168.32       0
Bank Sta=7363.663,15020.8
Exp/Cntr=0.3,0.1

Type RM Length L Ch R = 1 , 21266.2,932.303100,932.303100,932.303100
XS GIS Cut Line= 6
409762.451022655 756694.79987441410310.991576493756170.089494184
 410675.58501187755612.479277924410846.204457253755145.479576856
411112.218236685 754636.40367718412907.330818057750046.560351491
#Sta/Elev= 30
7986.167202.47228437.839183.54998550.182173.53469066.728102.25649356.23742.16612
9509.89726.037999837.73325.552919983.61630.30016   1000125.9774110036.5432.54715
10117.32 27.283511027.5929.8986911100.8425.2121411188.6630.3307811446.3624.80427
13078.4829.1771614495.8442.9809214549.5341.5637314571.0132.08265 14624.742.78269
14860.9241.2524314893.14 46.228714925.35 39.727715000.5135.83221 15054.242.62906
15081.75 37.367615161.5841.7161215191.5748.5219915247.48 47.7349 15417.682.22631
#Mann= 3 , 0 , 0
7986.167   0.045       07986.167   0.045       0 15417.6   0.045       0
#XS Ineff= 2 , 0
       09702.151         12074.3       0
Bank Sta=7986.167,15417.6
Exp/Cntr=0.3,0.1

Type RM Length L Ch R = 1 ,20333.89,0.000000,0.000000,0.000000
XS GIS Cut Line= 6
410883.291625708 756395.06037052411566.870613217755699.992989257
412332.750378221754474.602162838412736.396211565753419.914662838
413232.021987587750593.451414719413355.988984704750182.512398526
#Sta/Elev= 30
8982.771120.77319180.604 103.707 9315.3683.17535 9391.7564.860169454.17955.76793
9583.40751.086849717.57635.12826 9878.6728.118789978.68930.8826210003.1425.42304
10075.9531.5331210229.7425.1591610313.87 29.906212157.6225.9761913856.5531.73943
14312.8739.4238114505.2236.0147414606.4645.7772314646.9645.0655214677.3338.99634
14748.1938.3705415031.6644.3874615183.5252.3169515244.2663.72958 15345.594.50639
15406.25102.182315447.9897.8434615573.3265.5138115656.8851.1315115837.0448.78168
#Mann= 3 , 0 , 0
8982.771  0.0449       08982.771  0.0449       015837.04  0.0449       0
#XS Ineff= 2 , 0
       09821.098        12333.39       0
Bank Sta=8982.771,15837.04
Exp/Cntr=0.3,0.1